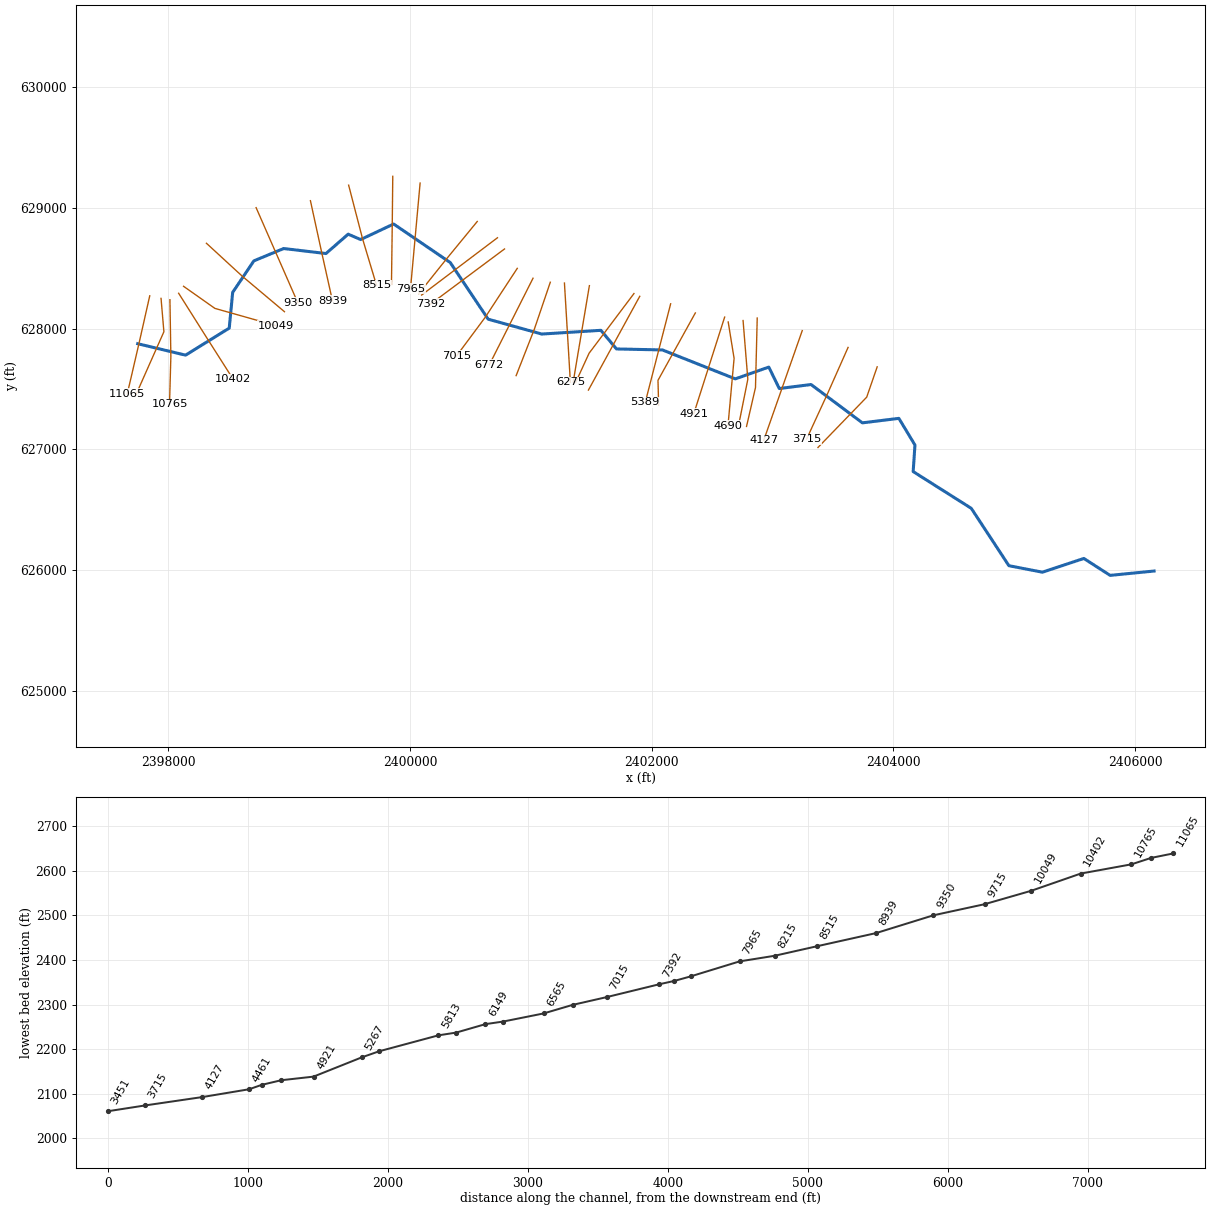
--- LAURELRN.prj (project) ---

Proj Title=LAURELRN
Current Plan=p01
Default Exp/Contr=0,0
English Units
Geom File=g01
Flow File=f01
Plan File=p01
BEGIN DESCRIPTION:
Stream Name: Laurel Run
Flood Zone: Approximate
Pendleton County, West Virginia
HEC-RAS Version: 5.0.7
Hydrology Method:
Regression equation
END DESCRIPTION:
DSS Export Rating Curves= 0
DSS Export Rating Curve Sorted= 0
DSS Export Volume Flow Curves= 0
DXF OffsetX= 0
DXF OffsetY= 0
DXF ScaleX= 0
DXF ScaleY= 0

--- LAURELRN.p01 (plan) ---

Plan Title=Floodplain
Program Version=4.00
Geom File=g01
Flow File=f01
K Sum by GR=0
Std Step Tol=0.01
Critical Tol=0.01
Num of Std Step Trials=20
Max Error Tol=0.3
Flow Tol Ratio=0.001
Split Flow NTrial=30
Split Flow Tol=0.02
Split Flow Ratio=0.02
Log Output Level=0
Friction Slope Method=1
Unsteady Friction Slope Method=2
Unsteady Bridges Friction Slope Method=1
Global Log Level=0
CheckData=False
Run HTab=0
Run UNet=0
Run PostProcess=0
UNET Theta=0
UNET Theta Warmup=0
UNET ZTol=0
UNET ZSATol=0
UNET MxIter=0
UNET MaxInSteps=0
UNET DtIC=0
UNET DtMin=0
UNET MaxCRTS=0
UNET WFStab=0
UNET SFStab=0
UNET WFX=0
UNET SFX=0
UNET DSS MLevel=0
UNET DZMax Abort=0
UNET Convert EG Bridges=0
UNET Use Existing IB Tables=0
UNET Froude Limit=0
UNET Froude Power=0
Write IC File=0
Echo Input=False
Echo Output=False
Write Detailed=0

--- LAURELRN.f01 (steady flow) ---

Flow Title=Flows
Program Version=5.07
Number of Profiles= 6
Profile Names=P100yr,P10yr,P25yr,P50yr,P500yr,P101yr
River Rch & RM=LAURELRN,Main            ,11065
     739     344     488     610    1086     899
River Rch & RM=LAURELRN,Main            ,9715
     839     390     553     692    1234    1021
River Rch & RM=LAURELRN,Main            ,8515
     987     458     650     814    1456    1202
River Rch & RM=LAURELRN,Main            ,7015
    1099     509     723     905    1622    1338
Boundary for River Rch & Prof#=LAURELRN,Main            , 1
Up Type= 0
Dn Type= 3
Dn Slope=0.06823
Boundary for River Rch & Prof#=LAURELRN,Main            , 2
Up Type= 0
Dn Type= 3
Dn Slope=0.06823
Boundary for River Rch & Prof#=LAURELRN,Main            , 3
Up Type= 0
Dn Type= 3
Dn Slope=0.06823
Boundary for River Rch & Prof#=LAURELRN,Main            , 4
Up Type= 0
Dn Type= 3
Dn Slope=0.06823
Boundary for River Rch & Prof#=LAURELRN,Main            , 5
Up Type= 0
Dn Type= 3
Dn Slope=0.06823
Boundary for River Rch & Prof#=LAURELRN,Main            , 6
Up Type= 0
Dn Type= 3
Dn Slope=0.06823
DSS Import GetInterval= 0
DSS Import GetPeak= 0
DSS Import FillOption= 0

--- LAURELRN.g01 (geometry) ---

Geom Title=Geometry
Program Version=5.07

River Reach=LAURELRN        ,Main
Reach XY= 30
     2397747.444       627875.26     2398143.605      627780.381
     2398504.986      628004.169     2398533.483      628300.375
     2398709.038       628561.24     2398955.668      628663.384
      2399305.28      628621.819     2399489.392      628782.233
     2399592.717      628737.784     2399865.456      628866.488
     2400333.545      628547.532     2400647.636      628078.202
     2401091.606      627955.071     2401580.598      627985.992
     2401709.371      627831.731     2402089.962      627823.509
     2402692.714      627583.909     2402970.304      627681.511
     2403056.736      627503.923     2403319.426      627537.137
     2403744.436      627219.843     2404046.481      627256.743
     2404179.443      627036.152     2404164.671      626816.264
     2404645.387      626511.902      2404956.91      626036.808
     2405234.054      625982.927     2405577.079      626096.724
       2405794.8      625956.516     2406158.272        625992.5

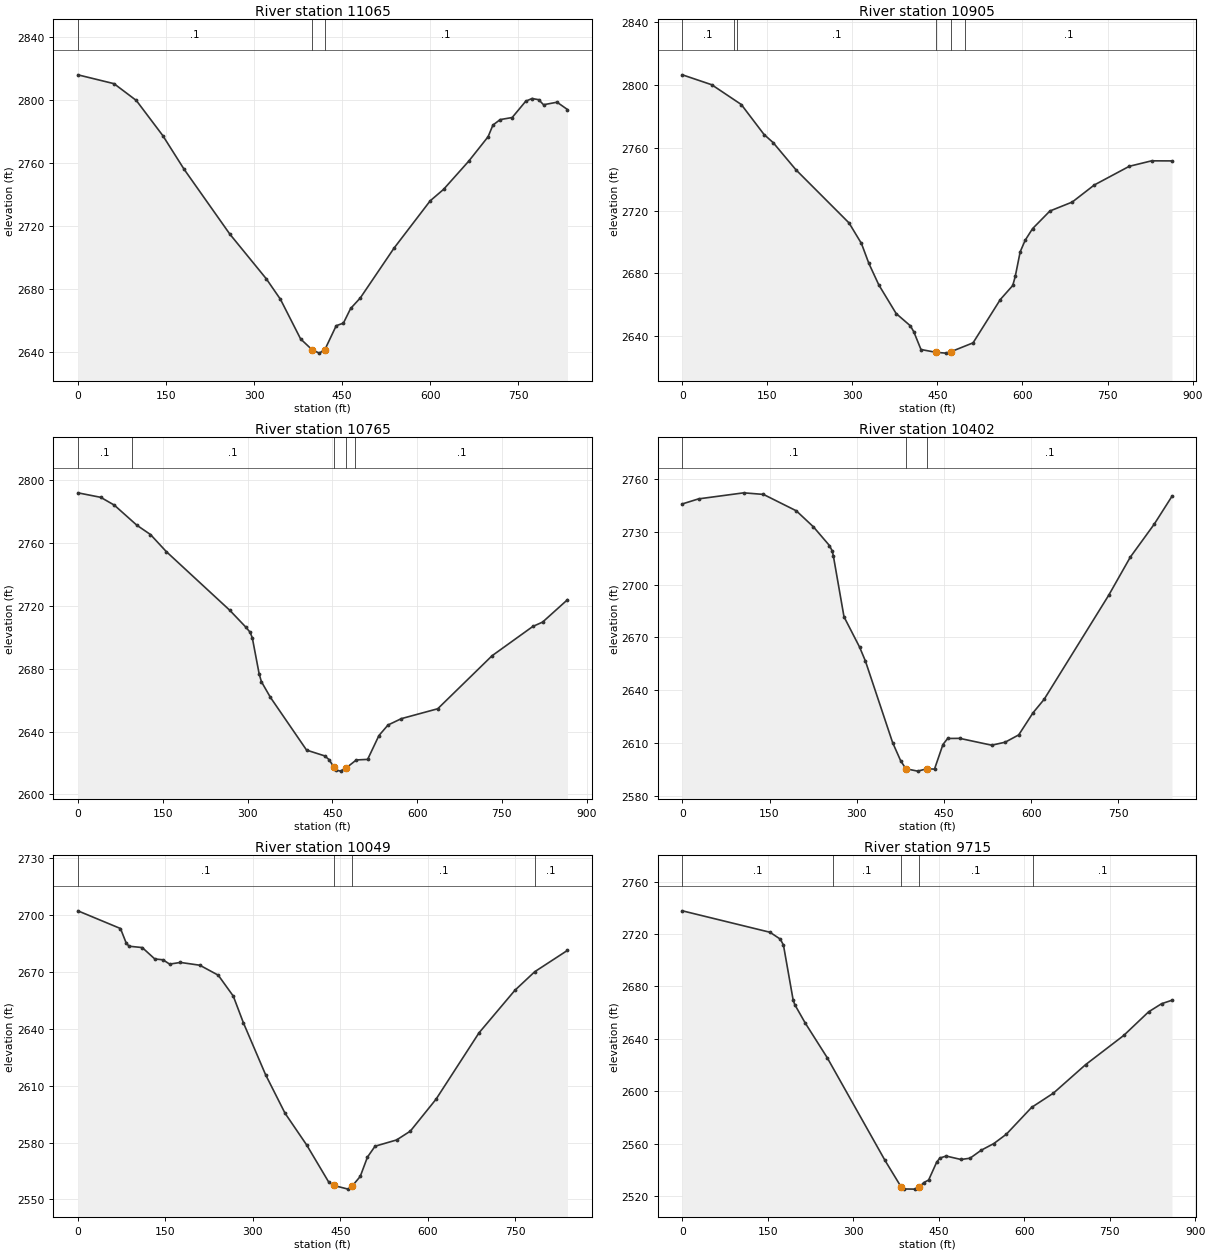
Type RM Length L Ch R = 1 ,11065   ,159.6,159.4,155.7
XS GIS Cut Line= 3
     2397847.198      628271.912     2397757.198      627873.059
2397661.09103096627459.171275904
#Sta/Elev= 30
       0 2815.83    61.5 2810.22    99.5 2799.56   144.6 2777.27   180.8 2755.96
   258.8 2714.76   320.9 2686.41     345  2673.4   379.3 2648.28   398.8 2641.44
   411.1 2639.28   420.62641.486   439.9 2656.66   452.2 2658.34   464.5 2667.61
   480.9 2674.27   538.4  2705.9     600 2735.91   622.7 2743.15   665.7  2761.1
   698.6 2776.57   706.8 2783.94   719.1 2787.42   739.6 2788.75   762.7 2799.08
   773.4 2800.81   784.8 2800.05     793 2796.85     816 2798.46   833.8 2793.81
#Mann= 3 ,-1 , 0
       0      .1       0   398.8    .045       0   420.6      .1       0
Bank Sta=398.8,420.6
XS Rating Curve= 0 ,0
Exp/Cntr=0.3,0.1

Type RM Length L Ch R = 1 ,10905   ,133.9,140.6,143.8
XS GIS Cut Line= 3
2397940.69512118628250.4620003872397964.29224994627974.038492028
2397726.63545312627438.046567284
#Sta/Elev= 30
       0 2806.45    51.8 2800.13   103.9 2787.55   144.1 2768.44   160.2 2763.26
   200.3 2745.98     294 2712.12   315.9 2699.03     329 2686.34   346.5 2672.68
   377.1 2654.43   402.2 2646.59   408.3 2642.76   420.9 2631.52   447.1 2629.73
   464.6 2629.21   473.4 2630.06   512.8 2635.76   560.9 2663.36   582.8 2672.28
   587.2 2678.03   595.9 2693.69   604.7 2701.08   617.8 2708.51   648.4 2719.73
   687.8 2725.43   726.6 2736.28   788.4  2748.2   827.8 2751.68   863.7 2751.63
#Mann= 6 ,-1 , 0
       0      .1       0   90.56      .1       0   96.28      .1       0
   447.1    .045       0   473.4      .1       0  499.21      .1       0
Bank Sta=447.1,473.4
XS Rating Curve= 0 ,0
Exp/Cntr(USF)=0,0
Exp/Cntr=0.3,0.1

Type RM Length L Ch R = 1 ,10765   ,351.4,362.7,365.2
XS GIS Cut Line= 3
 2398014.2638237  628239.3094751     2398021.958      627771.756
     2398010.852        627373.5
#Sta/Elev= 30
       0 2792.02    40.4 2789.15    64.4 2784.19   104.4 2771.36   128.4 2765.46
   156.4 2754.58   268.5 2717.28   296.9 2706.55   304.5 2703.28   308.5 2699.71
   320.5 2676.94   324.5 2671.82   340.5  2661.8   404.5 2628.19   436.5 2624.51
   444.5 2622.06   452.5 2617.44   456.5 2615.53   464.5  2614.8   475.12616.981
   492.5 2621.92   512.5 2622.28   532.5 2637.47   548.5 2644.16   572.2 2648.23
   636.5 2654.52   732.6 2688.28   804.6 2706.91     822 2709.71     866 2723.96
#Mann= 5 ,-1 , 0
       0      .1       0   95.19      .1       0   452.5    .045       0
   475.1      .1       0  490.92      .1       0
Bank Sta=452.5,475.1
XS Rating Curve= 0 ,0
Exp/Cntr=0.3,0.1

Type RM Length L Ch R = 1 ,10402   ,328.4,353.1,356.7
XS GIS Cut Line= 3
     2398086.419      628292.8852398303.32172811627948.851588153
     2398537.211       627581.28
#Sta/Elev= 30
       0 2745.93    27.8 2748.79   105.6 2752.23   139.5 2751.33     196 2742.01
   225.6 2732.85     253 2722.28   257.7 2719.27   259.8 2716.31   278.1 2681.75
     305 2664.46   314.9 2656.62   361.7 2610.28   375.6  2599.9   384.5 2595.37
   404.8 2594.02   420.5 2595.33   433.8 2595.17   448.3 2609.13   456.4 2612.58
   477.2 2612.65   532.3 2608.75   555.5 2610.48   578.7 2614.62   603.4 2627.22
   622.4 2634.82   733.5 2693.99   770.7 2715.68     812 2734.48   842.4 2750.27
#Mann= 3 ,-1 , 0
       0      .1       0   384.5    .045       0   420.5      .1       0
Bank Sta=384.5,420.5
XS Rating Curve= 0 ,0
Exp/Cntr=0.3,0.1

Type RM Length L Ch R = 1 ,10049   ,342.1,334.2,329.6
XS GIS Cut Line= 3
     2398127.083      628350.4652398386.23044277628167.632049799
2398888.69791386628025.604388956
#Sta/Elev= 30
       0 2702.13      73  2692.8    82.8 2685.17    87.7 2683.48   110.3 2682.77
   131.8 2676.77   145.8 2676.32   157.3 2674.05   175.8 2674.93     209 2673.46
   240.6 2668.21   266.4 2657.18   283.7 2643.13   321.8 2615.74   355.1 2595.46
   392.2 2578.72   429.9 2559.21   438.5  2557.4   463.2 2555.46   470.5 2557.19
     484 2562.14   496.4 2572.35   509.4 2578.07   546.3 2581.37   569.9 2586.03
     614 2602.87   687.6 2637.82   749.2 2660.27   783.2 2670.05   839.3 2681.29
#Mann= 4 ,-1 , 0
       0      .1       0   438.5    .045       0   470.5      .1       0
  783.07      .1       0
Bank Sta=438.5,470.5
XS Rating Curve= 0 ,0
Exp/Cntr=0.3,0.1

Type RM Length L Ch R = 1 ,9715    ,368.8,364.8,357.9
XS GIS Cut Line= 3
     2398316.181       628706.93     2398614.674      628432.487
     2398961.986      628140.311
#Sta/Elev= 30
       0 2737.71   153.7 2721.35   171.9  2716.1   177.4 2711.54   194.3  2669.9
   197.2 2666.16   215.4 2652.21   254.2  2625.6   355.7 2547.12     384  2526.9
   389.7 2525.38     408 2525.26   415.2 2526.63   423.7 2530.26   432.2  2532.2
   446.4 2545.92   452.1 2549.04   463.1 2550.51     489 2547.88   504.9 2548.87
   524.6 2554.99   546.7 2560.07   568.5 2567.14     613 2587.67   651.3 2598.57
   707.6 2620.25   774.6 2642.57   818.3  2660.6     841 2666.79   859.3 2669.46
#Mann= 5 ,-1 , 0
       0      .1       0  264.74      .1       0     384    .045       0
   415.2      .1       0  615.67      .1       0
Bank Sta=384,415.2
XS Rating Curve= 0 ,0
Exp/Cntr=0.3,0.1

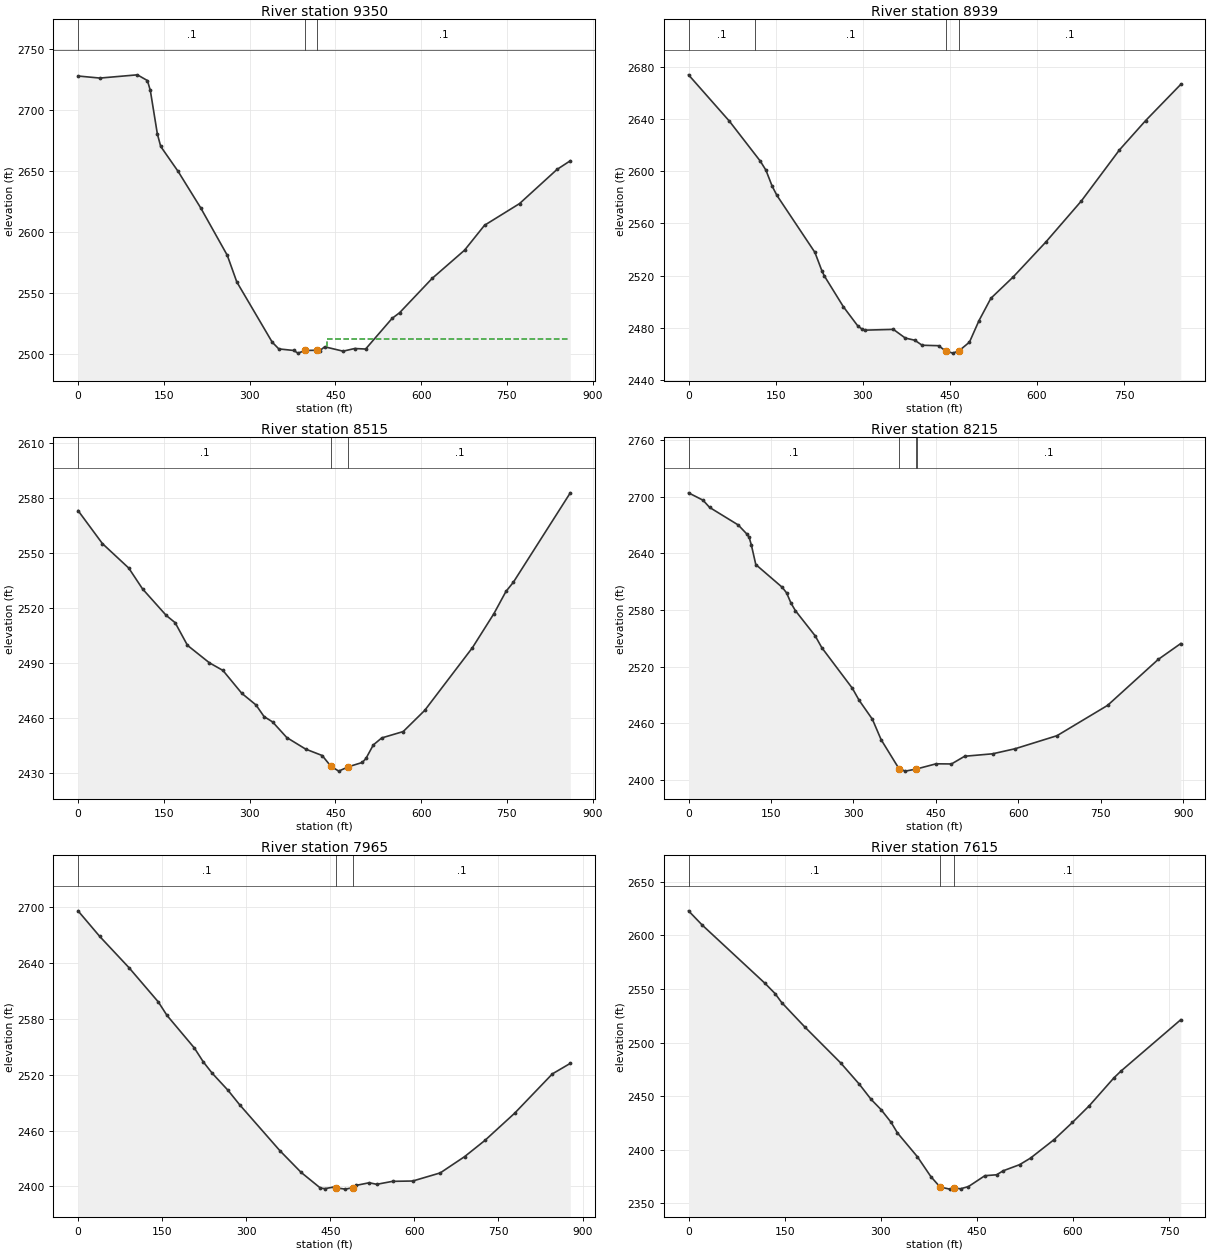
Type RM Length L Ch R = 1 ,9350    ,409.4,411,405.6
XS GIS Cut Line= 2
2398727.32671199629001.9677240962399072.76671199628213.532724096
#Sta/Elev= 30
       0 2727.84    38.3 2726.15   103.8 2728.81   121.3 2724.11   126.4 2716.03
   138.7 2680.33   144.6 2670.03     175 2649.57   214.5 2619.63     261 2580.69
   277.6 2558.88   339.6 2509.39   351.1  2503.9   377.3 2502.61   384.5 2500.44
   397.62502.652   418.2 2502.77   422.6 2502.41   431.3 2505.65   463.5 2502.04
   483.7 2504.22   502.9  2503.8   549.2 2528.96   562.3 2533.59   619.1  2561.7
   675.9 2584.92   710.8 2605.35     772 2623.13   837.5 2651.15   860.8 2658.29
#Mann= 3 ,-1 , 0
       0      .1       0   397.6    .045       0   418.2      .1       0
#XS Ineff= 2 , 0
                           435.1         2512.06
Permanent Ineff=
       F       F
Bank Sta=397.6,418.2
XS Rating Curve= 0 ,0
Exp/Cntr=0.3,0.1

Type RM Length L Ch R = 1 ,8939    ,420.3,424.2,421.3
XS GIS Cut Line= 3
 2399176.8377241629059.540681024 2399272.4007241628620.276681024
2399358.89362048628231.690779277
#Sta/Elev= 30
       0 2674.18    70.3 2638.62   123.5 2607.94   133.3 2600.93   143.9 2588.77
   152.1 2581.63   217.6 2537.81   229.9 2523.34   234.1 2519.54   266.7    2496
   291.3 2481.39   299.5 2478.58   304.7 2478.08   352.7 2478.66   373.2    2472
   389.6 2470.32   402.2 2466.48   430.5 2466.13   442.8 2462.05   455.1 2460.42
   466.1 2462.33   483.7 2468.86   500.1 2485.36   520.6 2502.54     559 2518.92
   614.9 2545.59   676.3 2577.25   741.9 2616.47     787 2639.01   847.6 2666.87
#Mann= 4 ,-1 , 0
       0      .1       0  115.26      .1       0   442.8    .045       0
   466.1      .1       0
Bank Sta=442.8,466.1
XS Rating Curve= 0 ,0
Exp/Cntr=0.3,0.1

Type RM Length L Ch R = 1 ,8515    ,299.4,300,289.7
XS GIS Cut Line= 3
     2399493.049      629188.151     2399608.465      628743.247
      2399723.84      628359.063
#Sta/Elev= 30
       0 2573.07    42.6 2555.03    88.7 2541.65   112.9 2530.24   154.2  2515.8
   169.8 2511.84   191.4 2499.45   229.8  2489.9   253.4 2485.75   286.4 2473.24
   311.2  2466.9   325.3 2460.56   340.2 2457.64     365 2449.11     398  2442.8
   426.9  2439.3   442.1 2433.45   455.9 2430.77   472.5 2433.13   497.1  2435.5
   503.5 2437.71   516.3 2445.06     531 2448.89   568.6 2452.38   606.2 2463.93
   689.6 2498.16   727.3 2516.81   748.2 2528.86   761.2  2533.9   860.8 2582.74
#Mann= 3 ,-1 , 0
       0      .1       0   442.1    .045       0   472.5      .1       0
Bank Sta=442.1,472.5
XS Rating Curve= 0 ,0
Exp/Cntr=0.3,0.1

Type RM Length L Ch R = 1 ,8215    ,245.3,250.2,241.1
XS GIS Cut Line= 3
     2399858.268      629261.274      2399854.03      628867.437
2399847.49776672628365.739963211
#Sta/Elev= 30
       0 2703.93    26.4 2696.12    38.4 2688.49    90.4 2669.94   106.4 2660.19
   110.4 2656.69   114.4 2648.53   122.4 2628.05   170.4 2604.04   178.4 2598.13
   186.4 2587.31   194.4 2579.33   230.4 2552.69   242.4 2540.22   298.1 2497.17
   310.4 2484.49   334.5 2464.44   350.4 2442.85     383 2412.07   394.4 2409.57
   414.4 2411.77   450.4 2417.31   478.4 2417.15   502.4 2425.31   553.2 2427.89
   594.4 2433.29   670.4 2447.05   762.4 2479.12   854.4 2527.66   895.6 2544.56
#Mann= 4 ,-1 , 0
       0      .1       0     383    .045       0   414.4      .1       0
  415.78      .1       0
Bank Sta=383,414.4
XS Rating Curve= 0 ,0
Exp/Cntr=0.3,0.1

Type RM Length L Ch R = 1 ,7965    ,353.6,349.8,337.7
XS GIS Cut Line= 2
2400084.54594195 629205.540211842400004.97621322628331.098099325
#Sta/Elev= 30
       0 2696.21    38.8 2668.62      91 2635.03   143.2 2598.26   158.7 2583.76
   207.5 2548.75   223.6 2533.66   239.5  2521.5   267.8 2503.07   288.1 2487.84
   360.1  2438.3     398 2414.96   432.4 2398.11   440.5 2397.52   456.5 2399.29
   460.5 2398.42   460.5  2398.4   476.6 2396.99   490.1 2398.55   496.7 2401.09
   519.5 2403.85   532.8 2402.17     561 2405.36   597.1 2405.72   646.1 2414.43
   689.5 2431.91   725.7 2449.32   778.6 2478.49   846.1  2520.9   878.1 2532.22
#Mann= 3 ,-1 , 0
       0      .1       0   460.5    .045       0   490.1      .1       0
Bank Sta=460.5,490.1
XS Rating Curve= 0 ,0
Exp/Cntr=0.3,0.1

Type RM Length L Ch R = 1 ,7615    ,117.8,115.4,111.9
XS GIS Cut Line= 3
     2400557.367      628887.276     2400301.185      628575.118
2400073.70331591628290.248040354
#Sta/Elev= 30
       0 2623.01    21.2 2609.83   119.5 2555.29     135 2545.86   145.4 2537.44
   181.6 2514.58   237.4 2481.16   266.5  2461.3   285.1    2447   300.6 2437.48
   316.1 2425.74   326.1 2415.79   357.4 2393.43   378.2 2375.06   392.62365.304
   407.7 2363.32   414.1 2364.32   424.6 2363.64     437 2365.74   462.6 2375.86
   480.9  2376.7   491.1 2380.42   516.7 2386.12   533.8 2392.27   570.8 2409.61
   599.3  2425.6   625.7 2441.23   664.1 2467.22   675.4 2473.68   768.4 2521.43
#Mann= 3 ,-1 , 0
       0      .1       0   392.6    .045       0   414.1      .1       0
Bank Sta=392.6,414.1
XS Rating Curve= 0 ,0
Exp/Cntr=0.3,0.1

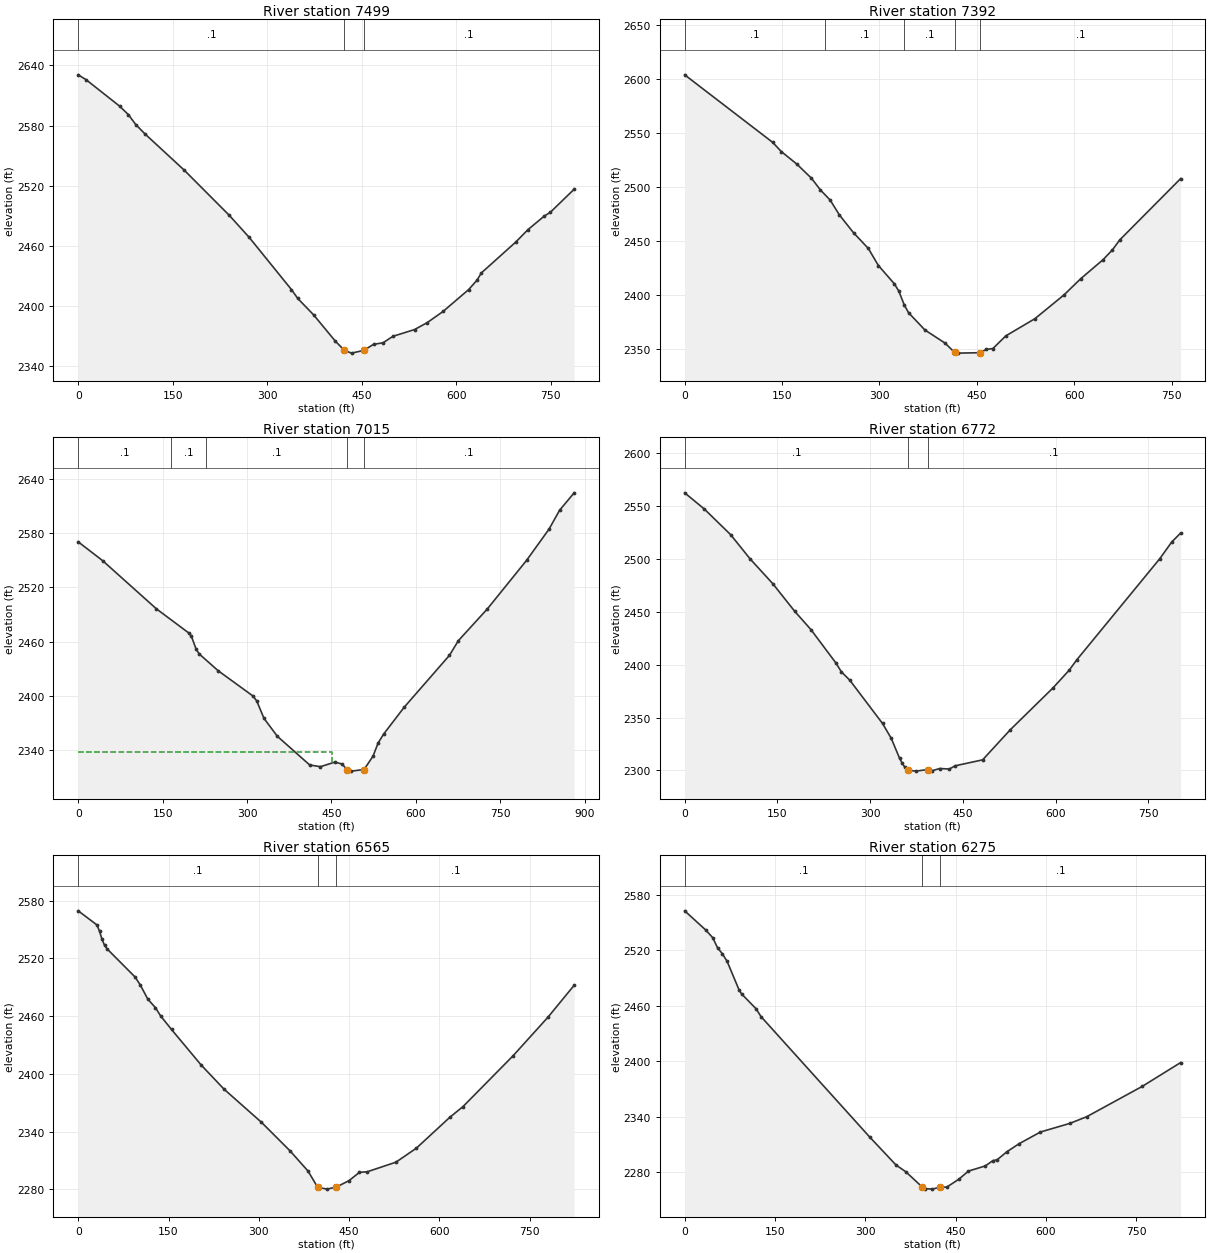
Type RM Length L Ch R = 1 ,7499    ,107,107.7,107.3
XS GIS Cut Line= 2
2400724.78468409628752.695579554 2400096.7831053 628278.03001422
#Sta/Elev= 30
       0 2630.68    12.6 2625.79    65.6 2599.52    79.8 2590.89    91.3 2581.14
   105.5 2572.06   168.4 2535.57   239.8  2490.6   271.2 2468.78   338.5 2416.58
   348.5 2407.74   373.6 2391.42   408.2 2365.12   422.5 2356.05   433.8 2353.24
     453 2355.94   468.9    2362   483.9 2363.55   499.6 2370.02   533.9 2376.74
   554.1  2383.7   579.2 2394.81   619.6 2416.52   633.2 2426.06   639.8 2433.13
   694.5 2463.96   713.8 2476.31   739.6 2489.77   749.6 2493.76   787.2 2516.65
#Mann= 3 ,-1 , 0
       0      .1       0   422.5    .045       0     453      .1       0
Bank Sta=422.5,453
XS Rating Curve= 0 ,0
Exp/Cntr=0.3,0.1

Type RM Length L Ch R = 1 ,7392    ,373.7,376.9,380.1
XS GIS Cut Line= 2
2400783.20980208628659.899145657     2400170.926628203.405159108
#Sta/Elev= 30
       0 2603.87   135.3 2541.33   148.9 2532.66   172.6 2521.13   195.2 2507.99
   209.1 2497.04     224 2487.74   238.3 2473.88     260  2457.4   282.8 2442.84
   298.3 2427.01   322.9 2410.03   329.8 2403.19   338.3 2390.21   344.8 2383.21
   369.8  2367.3   401.2 2354.94   415.5 2346.45   421.2 2345.75   454.6 2346.14
   464.6 2349.17   474.6 2350.02   494.5 2361.73   539.4 2377.73   583.9 2399.63
   609.9 2414.79   644.2 2432.38   658.5 2441.38   669.9 2450.71   763.7 2507.62
#Mann= 5 ,-1 , 0
       0      .1       0   216.3      .1       0   338.3      .1       0
   415.5    .045       0   454.6      .1       0
Bank Sta=415.5,454.6
XS Rating Curve= 0 ,0
Exp/Cntr=0.3,0.1

Type RM Length L Ch R = 1 ,7015    ,242.9,243.2,246.1
XS GIS Cut Line= 3
     2400888.524      628499.177     2400622.729      628092.969
     2400386.635      627774.941
#Sta/Elev= 30
       0 2570.19    43.4 2549.41     139 2496.16   196.3  2469.6   200.9 2466.35
   209.5  2451.7   215.3 2446.19   248.9  2427.7   311.1 2399.62   317.4 2394.25
   330.2 2375.12   353.9 2355.36   411.4 2323.64   430.6 2321.73   456.2 2326.82
   468.8 2324.72   477.92318.583   485.4 2316.83     508 2318.61   524.1 2333.47
   532.9 2347.74   542.8 2357.69   579.4 2387.44   659.9 2444.81   675.6 2460.92
   727.2 2496.08   796.9 2549.71   836.8 2584.18   855.7 2605.19   881.5 2624.36
#Mann= 5 ,-1 , 0
       0      .1       0  165.01      .1       0  227.03      .1       0
   477.9    .045       0     508      .1       0
#XS Ineff= 2 , 0
           450.8 2338.07
Permanent Ineff=
       F       F
Bank Sta=477.9,508
XS Rating Curve= 0 ,0
Exp/Cntr=0.3,0.1

Type RM Length L Ch R = 1 ,6772    ,203.6,206.8,205.7
XS GIS Cut Line= 2
2401018.90836167628417.2491061872400657.51868266627700.900169497
#Sta/Elev= 30
       0 2562.12    31.7 2546.87    74.3 2522.66   105.7 2499.86   142.5 2476.37
     178 2450.29   204.3 2432.98   244.6 2401.53   253.5 2393.14     267 2385.32
   320.1 2344.37   334.2  2330.3   347.6 2311.58   352.1 2306.67   356.2 2302.99
   361.92300.324   374.1 2299.39   392.92300.855   400.9 2299.89   412.8 2301.86
   428.3 2301.35   437.2 2304.38     482 2310.04   526.8 2338.49   595.4  2377.7
     622 2394.64   634.3 2404.44   768.8  2500.1     788 2515.75   802.3 2524.12
#Mann= 3 , 0 , 0
       0      .1       0   361.9    .045       0   392.9      .1       0
Bank Sta=361.9,392.9
XS Rating Curve= 0 ,0
Exp/Cntr(USF)=0,0
Exp/Cntr=0.3,0.1

Type RM Length L Ch R = 1 ,6565    ,282.6,290.3,295.6
XS GIS Cut Line= 3
     2401161.907      628384.383     2401030.026      627996.046
2400879.21419651627610.757318976
#Sta/Elev= 30
       0 2569.33    31.1 2554.67    35.4 2548.17    39.6 2539.59    43.8 2533.55
      48 2529.78    94.5 2500.56     103 2492.45   115.6 2477.63   128.3 2468.71
   136.8 2460.26     155 2446.06   204.3 2409.12   242.4 2383.98   304.4 2349.66
   352.2  2319.8   381.8 2298.97   397.8 2282.15   413.4 2280.22     429  2282.4
     450 2289.09   467.2 2297.67   480.1 2298.24   527.8  2308.2   561.7 2322.72
   617.5 2354.93   639.3 2366.01   722.3 2418.66   780.5 2458.91   823.9 2491.98
#Mann= 3 ,-1 , 0
       0      .1       0   397.8    .045       0     429      .1       0
Bank Sta=397.8,429
XS Rating Curve= 0 ,0
Exp/Cntr=0.3,0.1

Type RM Length L Ch R = 1 ,6275    ,128,125.6,121
XS GIS Cut Line= 2
2401278.96712383      628377.407     2401328.049      627555.059
#Sta/Elev= 30
       0 2562.86    34.6 2542.35    46.6 2533.84    54.6 2522.89    62.7 2516.38
    70.6 2508.09    90.7  2476.8    94.7 2472.95   118.7 2456.85   126.7 2448.59
   307.1 2318.45   351.1    2288   367.2  2280.8     395 2263.98   399.2 2262.53
   411.2 2261.96   424.8 2264.17   435.3  2264.1   455.3 2272.64   471.4 2281.47
   499.4 2287.05   511.4 2292.53   519.4 2293.89   535.3 2302.41   555.5 2311.06
     591 2323.72   639.7 2333.01   667.7 2340.22   759.9    2373   823.8 2398.79
#Mann= 3 ,-1 , 0
       0      .1       0     395    .045       0   424.8      .1       0
Bank Sta=395,424.8
XS Rating Curve= 0 ,0
Exp/Cntr=0.3,0.1

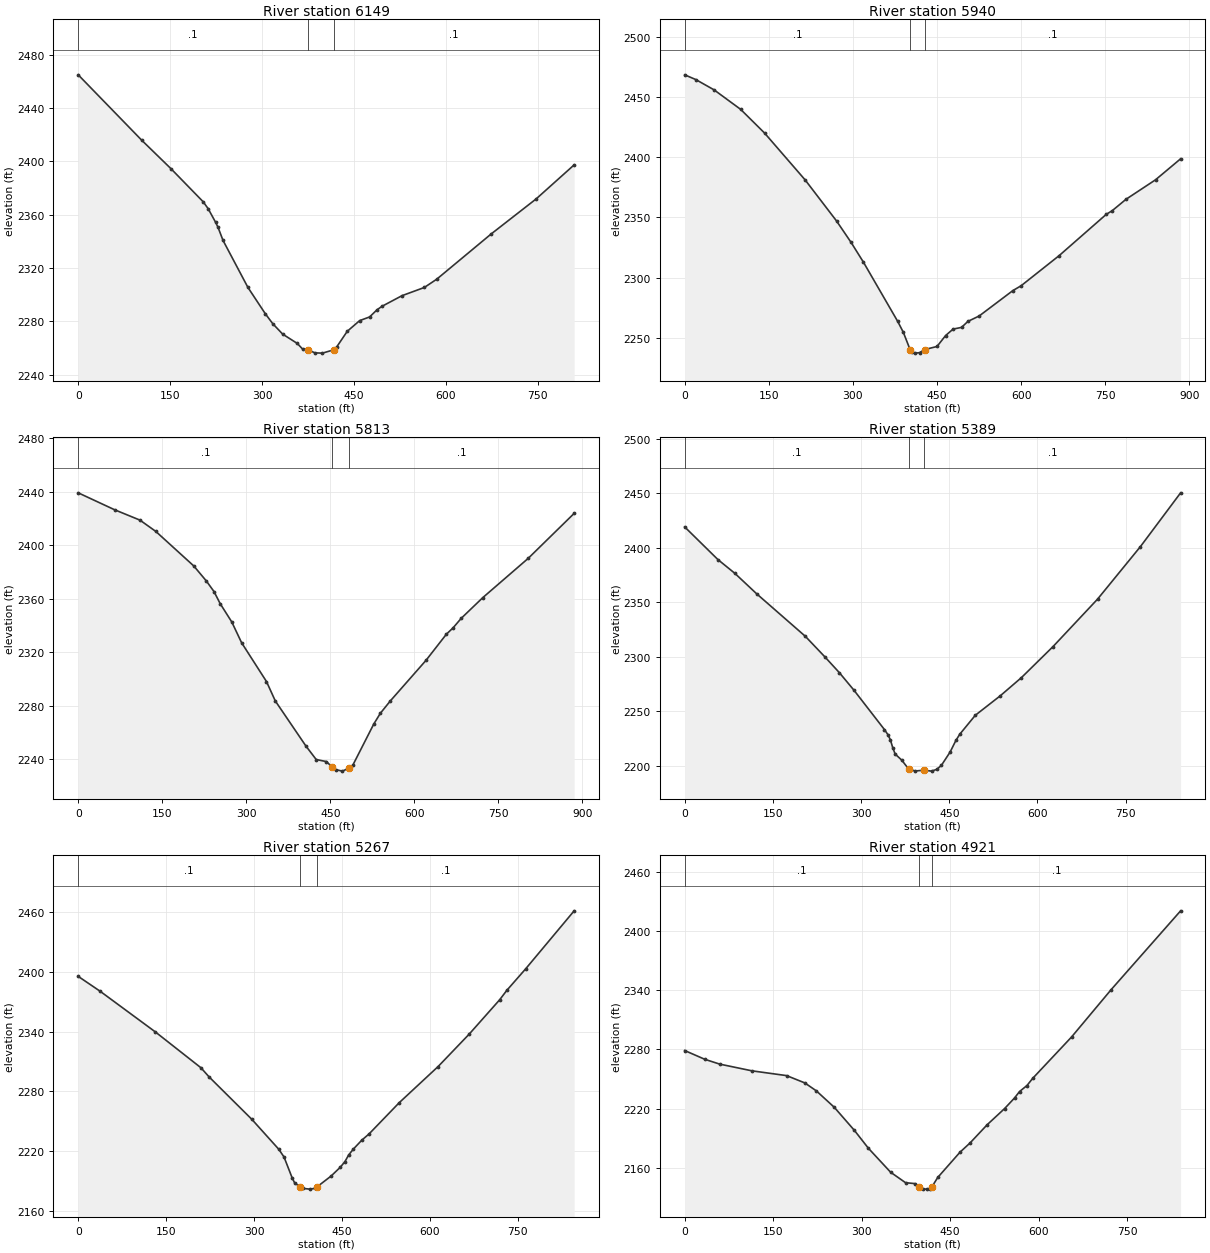
Type RM Length L Ch R = 1 ,6149    ,210.4,209,200.8
XS GIS Cut Line= 2
  2401485.401493628356.0735720662401351.36605606627557.629137421
#Sta/Elev= 30
       0 2464.88     104  2415.7   151.3 2394.56     204  2369.7   212.1 2364.54
   224.3  2354.3   228.3 2350.48   236.4 2340.73     277 2305.51   305.4 2285.77
   317.6 2278.28   333.8 2270.46   357.6 2263.49   366.2 2259.32   374.9  2258.7
   386.5 2256.42   398.7 2256.22   417.4 2258.74   422.3 2261.08   439.2 2272.59
   459.5 2280.61   475.7 2283.35   487.9 2288.76     496 2291.35   528.5 2299.28
     565 2305.44   585.3 2311.66   674.5  2345.7   747.5 2371.82   809.6 2397.37
#Mann= 3 ,-1 , 0
       0      .1       0   374.9    .045       0   417.4      .1       0
Bank Sta=374.9,417.4
XS Rating Curve= 0 ,0
Exp/Cntr(USF)=0,0
Exp/Cntr=0.3,0.1

Type RM Length L Ch R = 1 ,5940    ,123.4,127.4,128.6
XS GIS Cut Line= 3
2401854.27916375628290.6869374492401482.61590696627795.904369427
 2401371.9633973627554.359312922
#Sta/Elev= 30
       0 2468.44    19.8 2464.52    52.5 2455.93    99.8 2439.77   142.4 2420.12
   214.9 2381.11   270.9 2347.02   296.6 2329.37   318.9 2312.75     380 2263.57
     390 2254.51   402.3 2239.84     405 2237.93   410.9 2237.27   418.8 2237.65
     428 2240.23     450 2242.79   465.4 2251.89   478.7 2257.23   493.8 2258.65
     505 2263.59   525.2 2268.12   585.3 2289.21   600.1 2293.26   667.8 2318.24
   751.9 2352.55   762.6 2355.62   787.1 2365.06   839.8 2381.26   884.5 2398.69
#Mann= 3 ,-1 , 0
       0      .1       0   402.3    .045       0     428      .1       0
Bank Sta=402.3,428
XS Rating Curve= 0 ,0
Exp/Cntr=0.3,0.1

Type RM Length L Ch R = 1 ,5813    ,415.8,423.4,421.9
XS GIS Cut Line= 2
2401902.02191082628267.565611327 2401477.2735931627490.882973207
#Sta/Elev= 30
       0 2439.02    64.8  2426.4   110.2 2418.62   138.5 2410.18   206.3 2384.36
   228.7 2373.15   242.4 2365.21   253.4  2356.2   274.1 2342.51   291.7 2326.94
     336 2298.02   351.8 2283.48   406.5 2249.76   424.8  2239.7     443 2238.17
   453.8  2233.9   459.7 2232.14   471.5 2231.04     484 2233.41   490.4  2235.7
   527.5  2266.2   539.3 2274.27     557 2283.46   620.8 2313.84   657.2 2333.39
     669 2338.07   683.7 2345.26     722 2360.65   803.2 2390.05   885.2 2423.66
#Mann= 3 ,-1 , 0
       0      .1       0   453.8    .045       0     484      .1       0
Bank Sta=453.8,484
XS Rating Curve= 0 ,0
Exp/Cntr(USF)=0,0
Exp/Cntr=0.3,0.1

Type RM Length L Ch R = 1 ,5389    ,124.2,122.4,116.8
XS GIS Cut Line= 2
2402157.85069812628205.5610009812401947.50036204627388.670036789
#Sta/Elev= 30
       0 2419.29    56.5 2389.34    85.4 2376.68   122.5 2357.91   205.2 2318.96
   238.2 2300.24     263 2285.66   287.8  2269.6   339.8 2233.39   345.6 2228.82
   349.9 2223.96   353.8 2216.94     358 2210.97   369.3 2205.33   381.4 2196.88
   392.3 2195.46   407.5 2196.17   419.9 2195.31   428.5 2196.89   436.5 2200.49
   451.5 2212.85   461.3 2223.48   467.9 2229.16   494.3 2246.53   536.9 2264.45
   572.8  2281.1   626.5 2309.54   702.2 2353.03   775.2 2401.26   843.5 2450.54
#Mann= 3 ,-1 , 0
       0      .1       0   381.4    .045       0   407.5      .1       0
Bank Sta=381.4,407.5
XS Rating Curve= 0 ,0
Exp/Cntr=0.3,0.1

Type RM Length L Ch R = 1 ,5267    ,340.6,346.1,345.4
XS GIS Cut Line= 3
2402362.11356461 628129.97512247 2402052.9774137627571.715299427
     2402058.489       627364.05
#Sta/Elev= 30
       0 2395.61    37.1 2380.79   131.6 2339.79   209.3 2303.81     223 2294.75
   296.2 2251.95   341.9 2222.03     351 2214.18   364.7 2193.49   369.3 2187.93
   378.5 2184.28   378.5 2184.26     383 2182.61     395 2181.85   403.3 2182.55
   407.9 2184.36   431.4 2195.03     447 2203.84     455 2209.53   461.1    2216
   469.3 2222.09   483.6 2230.98   496.2 2237.38   547.6 2268.74   613.9 2305.04
     667 2337.67     719  2372.2     731 2381.54     763 2403.05   845.9 2461.47
#Mann= 3 ,-1 , 0
       0      .1       0   378.5    .045       0   407.9      .1       0
Bank Sta=378.5,407.9
XS Rating Curve= 0 ,0
Exp/Cntr=0.3,0.1

Type RM Length L Ch R = 1 ,4921    ,225.7,230.8,234.4
XS GIS Cut Line= 2
     2402604.665      628095.4992402349.17623958627294.813220723
#Sta/Elev= 30
       0 2278.86    34.2 2269.94    59.4 2265.09     114 2258.28   172.8 2253.44
   203.7 2246.02   223.2 2237.96   253.5 2221.37   287.8 2197.85   311.3 2179.89
   349.1 2155.53   374.3 2144.98   390.3 2144.04   396.7 2140.93   403.7 2138.55
   411.1 2138.45   415.8    2139     419  2140.8   428.9 2150.28   466.7 2175.92
   483.5 2185.13   512.9 2203.83   542.3 2220.12     559 2230.76   567.5 2237.29
   580.1  2243.4   589.9 2250.72   655.6 2292.52   722.8 2340.55   840.5 2420.37
#Mann= 3 ,-1 , 0
       0      .1       0   396.7    .045       0     419      .1       0
Bank Sta=396.7,419
XS Rating Curve= 0 ,0
Exp/Cntr=0.3,0.1

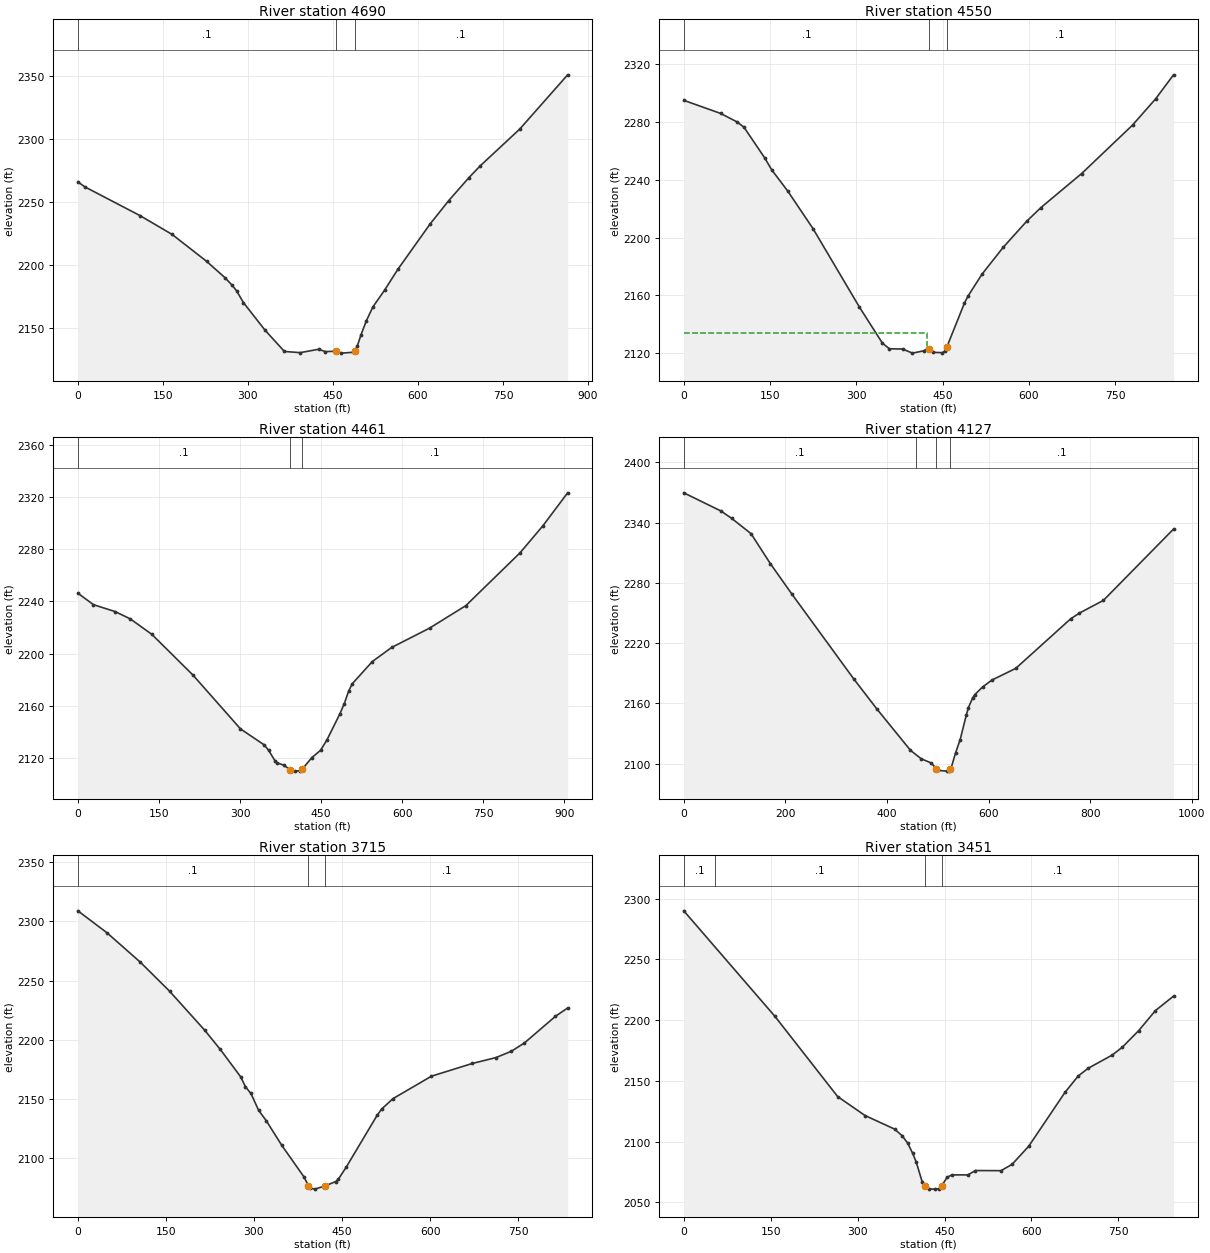
Type RM Length L Ch R = 1 ,4690    ,137.7,140.2,143.4
XS GIS Cut Line= 3
2402634.13465096628055.0696877242402682.82713888627753.550820205
2402632.26186296627197.332785093
#Sta/Elev= 30
       0 2266.09    12.3 2262.16   109.6 2239.37   166.3 2224.42   227.1  2203.1
   259.5 2190.14   271.7 2184.36   279.8 2179.84   291.9 2170.48     330 2148.59
   364.3 2131.67   392.2 2130.74   424.6 2133.41   436.6 2131.54   455.2 2131.89
   464.7 2130.35   484.7 2130.99   488.4 2132.06   492.9 2135.99   499.4 2144.93
   508.9 2156.06   520.3 2166.94   541.1 2180.35   564.5 2196.87   621.4 2232.81
     654 2251.18   689.7 2269.46   709.7 2278.81   779.2 2307.89   863.9 2350.98
#Mann= 3 ,-1 , 0
       0      .1       0   455.2    .045       0   488.4      .1       0
Bank Sta=455.2,488.4
XS Rating Curve= 0 ,0
Exp/Cntr(USF)=0,0
Exp/Cntr=0.3,0.1

Type RM Length L Ch R = 1 ,4550    ,90.6,89,92.8
XS GIS Cut Line= 3
2402757.06124207628067.1254085942402796.49712289627580.799874452
2402725.19270538627224.527200029
#Sta/Elev= 30
       0 2295.05    63.9 2285.99    92.5 2280.12   104.6 2276.44   140.7 2255.15
   152.7 2246.99   180.8 2232.14   224.5 2206.25   305.2 2151.89   345.4 2126.77
   357.4 2122.94   380.4 2122.75   397.5 2119.92   417.6 2121.55   425.6 2123.72
   426.92123.053   433.7 2120.44   449.7 2120.25   453.7  2121.2     457 2123.87
   487.9 2154.63   493.9 2159.34   518.4  2174.6   555.1 2193.16   595.9 2211.19
   620.7 2220.72   691.6 2244.33     780 2277.86   820.3 2296.14   851.3 2312.71
#Mann= 3 , 0 , 0
       0      .1       0   426.9    .045       0     457      .1       0
#XS Ineff= 2 , 0
          422.75 2133.52
Permanent Ineff=
       F       F
Bank Sta=426.9,457
XS Rating Curve= 0 ,0
Exp/Cntr(USF)=0,0
Exp/Cntr=0.3,0.1

Type RM Length L Ch R = 1 ,4461    ,330.9,333.8,331
XS GIS Cut Line= 3
  2402874.228832628087.6903299322402859.81942126627511.917086104
     2402785.767      627189.892
#Sta/Elev= 30
       0 2246.26    28.8 2237.49    68.8 2232.22    96.8 2226.66   136.8 2214.81
   212.9 2183.65   300.9 2142.45   344.9 2130.19   352.9 2126.13   364.9 2117.95
   368.9 2116.43   380.9 2114.72   392.9 2111.13   400.9 2110.13   411.7 2110.39
   415.42111.725   432.9 2120.44   449.2  2126.1     461 2134.09     485 2154.07
     493 2161.77     501 2171.27   507.7 2176.95     545    2194   580.7 2204.76
   650.9 2219.55   717.9 2236.74     818 2277.03   860.2 2297.65   906.4 2323.07
#Mann= 3 ,-1 , 0
       0      .1       0   392.9    .045       0   415.4      .1       0
Bank Sta=392.9,415.4
XS Rating Curve= 0 ,0
Exp/Cntr=0.3,0.1

Type RM Length L Ch R = 1 ,4127    ,407.2,412.1,405.7
XS GIS Cut Line= 2
2403246.83339165627983.8224468432402927.71922882627073.905873467
#Sta/Elev= 30
       0 2369.67    72.8 2351.69    94.2 2344.29   132.4 2329.03   170.5 2299.17
   212.9 2268.83   334.3 2184.67   380.5 2154.31   446.4 2113.32   467.3 2104.98
   487.2 2100.71   497.5 2095.03   501.2 2093.32   518.1 2092.62   522.4 2092.96
   524.9 2094.56   526.6 2096.08   535.1 2110.72   544.2 2123.96   556.3 2148.51
   560.5 2155.89   568.8 2165.58   573.2 2168.84   588.9 2176.65   607.1 2183.37
   653.6 2194.89   761.7 2244.23   779.1 2249.97   826.2 2262.59   964.3 2333.58
#Mann= 4 ,-1 , 0
       0      .1       0  457.51      .1       0   497.5    .045       0
   524.9      .1       0
Bank Sta=497.5,524.9
XS Rating Curve= 0 ,0
Exp/Cntr=0.3,0.1

Type RM Length L Ch R = 1 ,3715    ,267.3,263.4,256.9
XS GIS Cut Line= 3
     2403626.035      627844.366     2403461.381      627473.202
     2403282.415      627084.065
#Sta/Elev= 30
       0 2308.92    49.7  2290.3   106.6  2265.4   156.1 2241.06   215.8 2208.13
   242.3 2191.97   277.3 2168.63   285.5 2160.19   294.8 2154.52   307.9 2140.34
   321.1 2131.39   347.3 2110.73   385.5 2083.78   392.8 2076.43   395.4 2074.59
   403.7 2073.69   421.7 2076.52   439.4 2080.12   443.8 2082.12     457 2092.13
   509.9 2136.16   517.7 2141.46   536.8 2150.17   602.3 2169.13   672.1 2179.92
   712.4 2184.89   738.5 2190.24   760.8 2197.24   813.6 2219.76   834.4 2226.79
#Mann= 3 ,-1 , 0
       0      .1       0   392.8    .045       0   421.7      .1       0
Bank Sta=392.8,421.7
XS Rating Curve= 0 ,0
Exp/Cntr=0.3,0.1

Type RM Length L Ch R = 1 ,3451    ,474.3,471.4,474.6
XS GIS Cut Line= 3
     2403866.839      627683.3582403780.12686004627432.392597757
     2403377.027      627015.798
#Sta/Elev= 30
       0 2290.03   157.1 2203.23   265.5 2137.06   312.8 2121.42   363.7 2110.27
   376.8  2104.8   386.4 2098.68   394.9 2090.41   401.2 2083.06   411.3 2067.03
   415.82063.032   422.8 2060.86   434.3 2060.79   440.2 2061.01   444.92063.339
   454.3 2070.44   462.4 2072.51   490.3 2072.53   503.4  2076.1   547.6    2076
   566.6 2081.23   595.4 2096.18   657.9 2140.49   680.6 2153.92   697.5 2160.23
   739.2 2171.17   756.5 2177.56   785.2  2191.4     814 2207.87   845.2 2219.76
#Mann= 4 ,-1 , 0
       0      .1       0   53.96      .1       0   415.8    .045       0
   444.9      .1       0
Bank Sta=415.8,444.9
XS Rating Curve= 0 ,0
Exp/Cntr=0.3,0.1