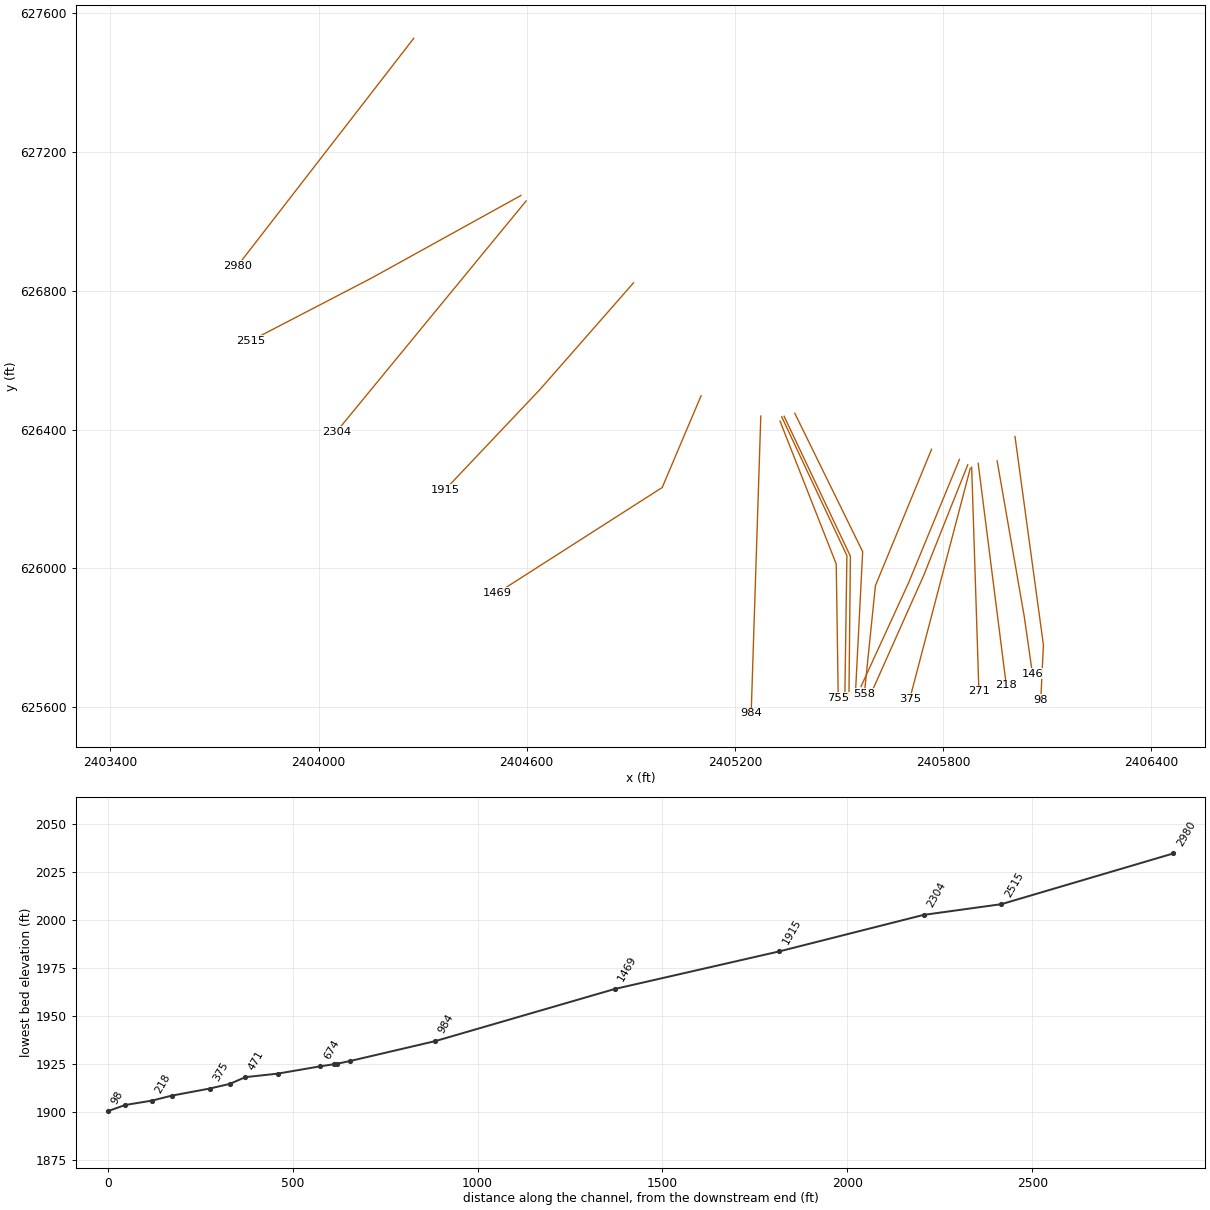
HEC-RAS study LAURELRN.prj: LAURELRN

--- LAURELRN.g01 (geometry) --- (continued)

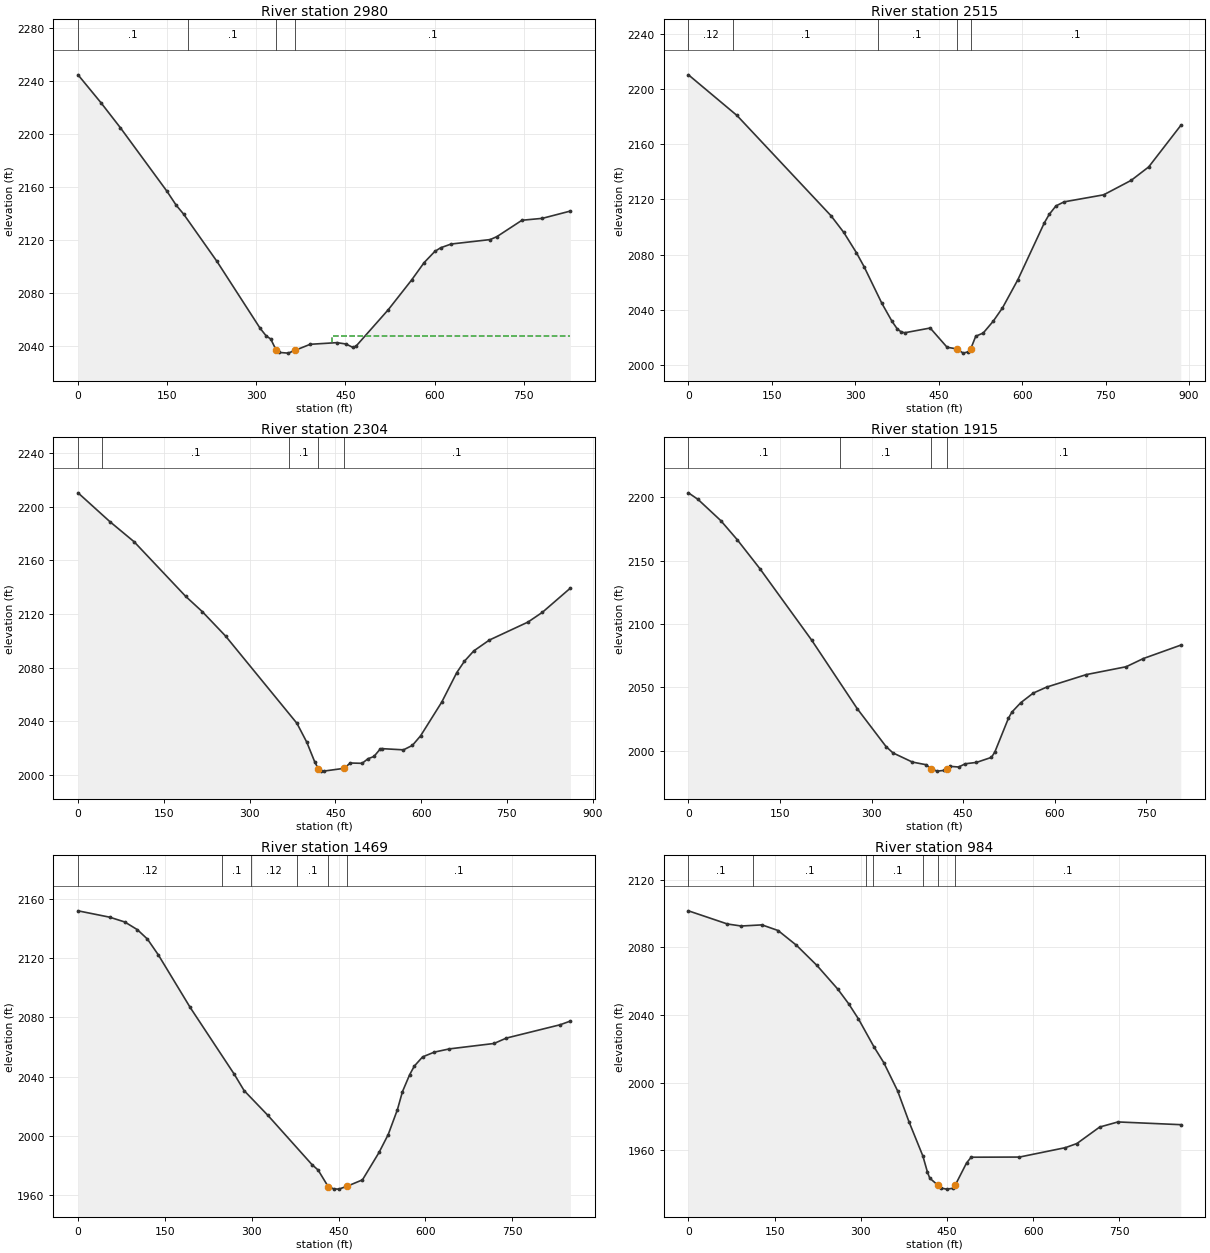
Type RM Length L Ch R = 1 ,2980    ,474.3,465.2,458.7
XS GIS Cut Line= 2
2404274.31709197627527.2787240812403767.03923913  626872.1998403
#Sta/Elev= 30
       0 2244.37    38.5 2223.41    71.2 2204.55   149.6 2156.68   165.3 2146.07
   177.6  2139.5   233.8 2103.82   306.4 2053.46   316.5 2047.77   324.3 2045.34
   333.6 2036.82     339 2035.25   353.5 2034.74   365.2 2036.81   390.6 2041.39
   435.6 2042.64   450.8 2041.63   461.9 2039.18   467.6 2039.89     522 2067.42
   561.2 2089.75   582.3 2102.89   600.3 2111.32   610.1 2114.08   627.8 2116.92
   693.6 2120.28   704.9 2122.51     747 2134.83   781.2 2136.26   828.5 2141.76
#Mann= 4 ,-1 , 0
       0      .1       0  185.59      .1       0   333.6    .045       0
   365.2      .1       0
#XS Ineff= 2 , 0
                          427.13            2048
Permanent Ineff=
       F       F
Bank Sta=333.6,365.2
XS Rating Curve= 0 ,0
Exp/Cntr=0.3,0.1

Type RM Length L Ch R = 1 ,2515    ,206.5,210.4,213.2
XS GIS Cut Line= 3
     2404583.158      627074.431     2404152.617      626836.417
2403803.51362584626655.091220723
#Sta/Elev= 30
       0 2210.61    87.3 2181.05   256.4 2108.16   279.3 2096.07   302.1 2081.27
   315.8 2071.18   347.8 2044.51   366.1  2031.4   375.3 2026.03   382.6  2023.7
     389 2023.13   434.7 2026.57     465 2012.61   482.7 2011.38   494.1 2008.32
   503.1 2009.32   507.6 2011.46   516.6  2020.6   530.1 2022.96   548.1 2031.57
   564.7 2041.21   592.4 2061.75   639.8 2102.92   648.7 2109.18   660.8 2115.32
   675.4 2118.27   746.6 2123.39   796.1 2133.91   827.6 2143.67   885.3 2173.85
#Mann= 5 ,-1 , 0
       0     .12       0    80.1      .1       0  339.99      .1       0
   482.7    .045       0   507.6      .1       0
Bank Sta=482.7,507.6
XS Rating Curve= 0 ,0
Exp/Cntr=0.3,0.1

Type RM Length L Ch R = 1 ,2304    ,386.7,389.6,386.9
XS GIS Cut Line= 2
2404598.20163795627058.6793620482404051.44804307626393.385067289
#Sta/Elev= 30
       0 2210.31    55.8 2188.78    98.1 2173.81   188.1 2133.17   217.2 2121.75
   258.1 2103.46   382.9 2038.37   400.2  2024.2   413.9 2009.71   420.1 2004.58
   424.3 2002.98   429.5 2002.74   465.3 2004.83   476.1  2008.8   496.8 2008.56
   507.1 2011.97   517.5 2013.66   527.8 2018.88   530.9 2019.52   569.2 2018.62
   584.8 2021.95   599.1 2029.07   636.1 2054.22   662.4 2076.25   675.8 2084.72
   692.1 2092.39   719.4 2100.51     787 2113.93   812.3 2121.25   861.1 2139.25
#Mann= 5 ,-1 , 0
       0     .12       0   41.59      .1       0   368.6      .1       0
   420.1    .045       0   465.3      .1       0
Bank Sta=420.1,465.3
XS Rating Curve= 0 ,0
Exp/Cntr=0.3,0.1

Type RM Length L Ch R = 1 ,1915    ,445.9,445.8,438.9
XS GIS Cut Line= 3
2404907.70824085626822.760759147     2404639.564      626517.036
2404364.58766892626226.542736205
#Sta/Elev= 30
       0 2203.69    15.8 2198.45      53 2181.73      80 2166.61   116.9 2143.87
     202 2087.22   276.5 2033.16   323.7 2003.22   335.1 1998.17   366.9 1990.93
   389.7  1988.8   397.4 1985.49   407.8 1983.77   419.5 1984.37   422.9 1985.81
   428.6 1987.57   442.7 1987.02   453.7 1989.59   471.9 1990.66   496.5 1994.65
   502.1 1998.98   524.2 2025.45     530 2030.45   544.6 2037.89     565 2045.46
     587 2050.19   652.1 2060.08   717.2 2066.26   745.3 2072.73   806.7 2083.35
#Mann= 4 ,-1 , 0
       0      .1       0  247.75      .1       0   397.4    .045       0
   422.9      .1       0
Bank Sta=397.4,422.9
XS Rating Curve= 0 ,0
Exp/Cntr=0.3,0.1

Type RM Length L Ch R = 1 ,1469    ,461,485,494.3
XS GIS Cut Line= 3
2405102.27040241626497.2553620482404990.33898253626233.074584137
     2404515.663      625929.277
#Sta/Elev= 30
       0 2151.81    54.7 2147.52    80.8 2144.28   102.5  2139.1   119.9 2132.76
   138.8 2122.05   193.7 2086.68     270 2041.56   286.9 2030.59   328.1 2013.84
     404 1980.75   414.7 1977.04     432 1965.93   441.7 1964.34   450.4 1964.16
   464.8 1966.11   491.3 1970.41   519.9 1988.86   535.8 2000.96   551.7 2017.75
   560.4 2029.89   572.9 2041.36   580.9 2047.12   595.2 2053.32   615.4 2056.54
   641.5 2058.72   718.6 2062.37   739.9 2066.01   832.6 2074.97   850.5 2077.48
#Mann= 6 ,-1 , 0
       0     .12       0   248.7      .1       0  299.59     .12       0
  378.26      .1       0     432    .045       0   464.8      .1       0
Bank Sta=432,464.8
XS Rating Curve= 0 ,0
Exp/Cntr=0.3,0.1

Type RM Length L Ch R = 1 ,984     ,221.4,229,233.7
XS GIS Cut Line= 2
     2405274.415      626438.781     2405246.672      625582.205
#Sta/Elev= 30
       0 2101.61    67.9 2093.82    91.9 2092.63     128  2093.3     156 2089.97
     188 2081.25   223.6 2069.35     260  2055.3   278.7 2046.75     296 2037.66
   322.8 2021.26   340.1 2011.78   364.1 1995.14   384.1  1976.7   408.1  1956.6
   416.1    1947   420.1 1943.52   433.7 1939.52   440.1 1937.65   449.3 1937.05
   460.1 1937.51   464.1  1939.2   484.1 1952.53   492.1 1955.92   576.2 1956.01
   656.2 1961.58   676.2 1964.02   715.8 1973.76   747.7 1976.78     857 1975.16
#Mann= 7 ,-1 , 0
       0      .1       0  113.13      .1       0  309.65      .1       0
  320.43      .1       0  407.91      .1       0   433.7    .045       0
   464.1      .1       0
Bank Sta=433.7,464.1
XS Rating Curve= 0 ,0
Exp/Cntr=0.3,0.1

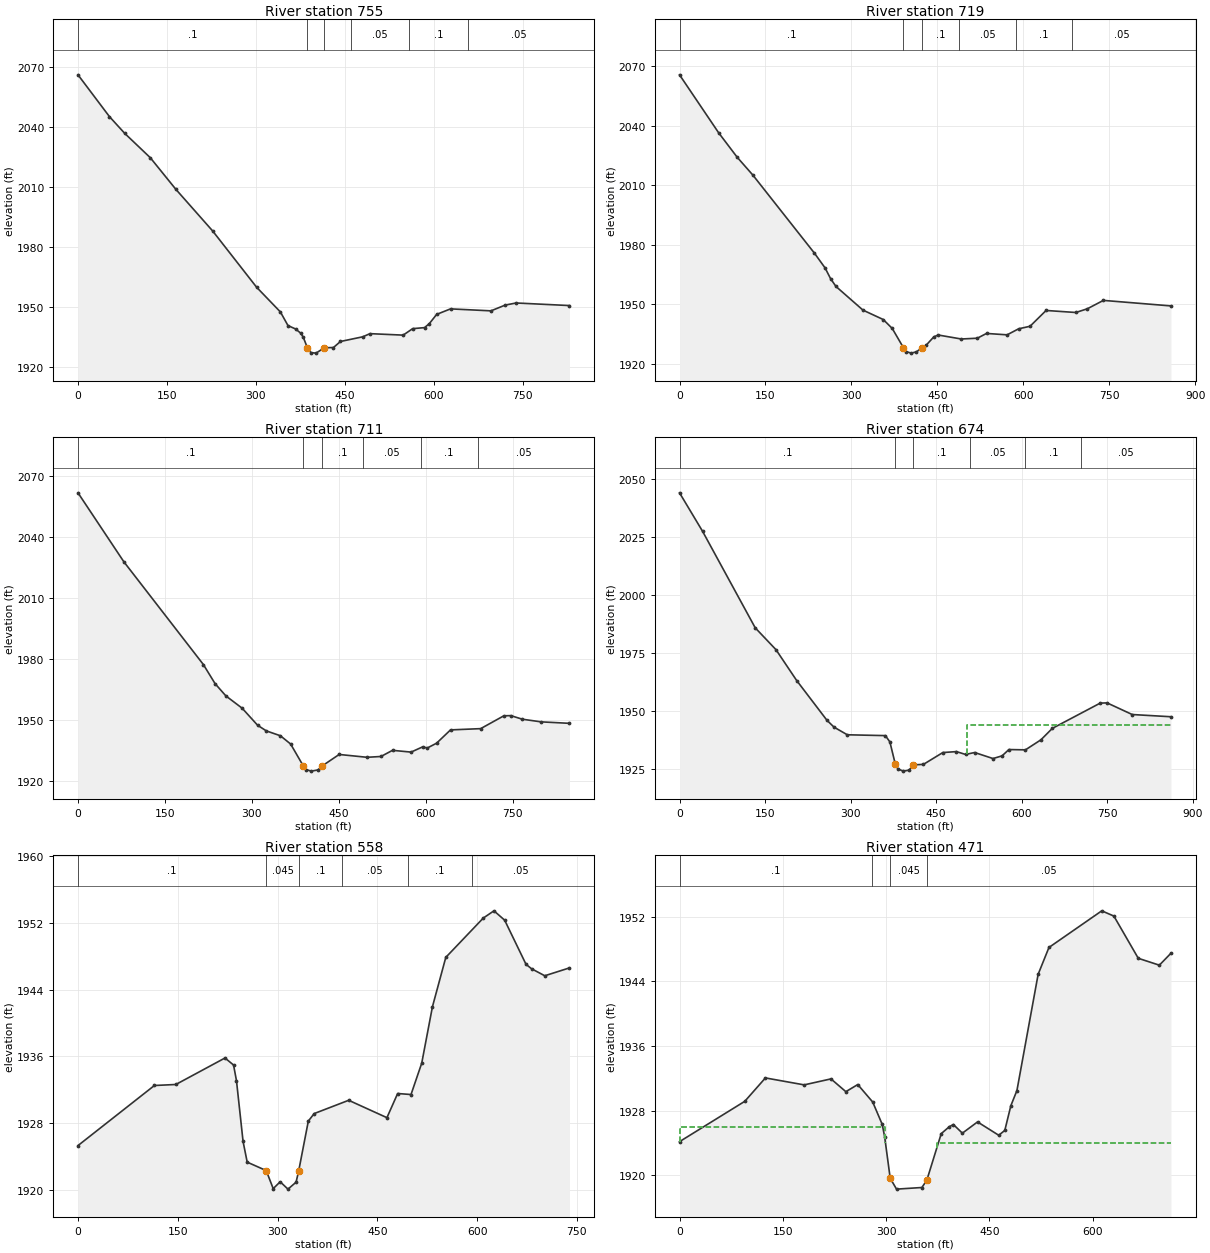
Type RM Length L Ch R = 1 ,755     ,34.8,35.8,36.4
XS GIS Cut Line= 3
2405329.77826808626424.346206236 2405491.7623197626012.593316175
2405497.56677123 625626.59728925
#Sta/Elev= 30
       0 2066.23    53.1 2045.26    78.9 2036.86   121.9 2024.69   164.9 2008.88
   227.1 1987.95   301.1 1959.78   341.2  1947.4     354 1940.56   366.9 1938.84
   375.5 1936.74   379.8 1934.69   386.71929.453   392.7 1926.99   401.3 1926.75
   415.2 1929.41   430.7 1929.57   442.5 1932.59   480.2 1934.94   492.2 1936.51
   548.2 1935.77   564.2 1939.02   584.2 1939.53   592.2 1941.51   604.7 1946.17
     628 1948.93   696.2 1947.94   720.2 1950.83   738.7 1951.88   828.5 1950.59
#Mann= 6 ,-1 , 0
       0      .1       0   386.7    .045       0   415.2      .1       0
  459.85     .05       0   558.8      .1       0  657.75     .05       0
Bank Sta=386.7,415.2
XS Rating Curve= 0 ,0
Exp/Cntr(USF)=0,0
Exp/Cntr=0.5,0.3

Type RM Length L Ch R = 1 ,719     ,8.2,8.3,8.4
XS GIS Cut Line= 3
2405334.64782153626436.7497245932405522.50334029626036.808028359
2405516.45585343625620.902853425
#Sta/Elev= 30
       0 2065.55    68.3 2036.33   100.7 2023.99   127.8 2015.09   235.4  1975.7
   254.1 1968.21   263.7 1962.79   273.1 1958.88   320.2 1946.96   355.6 1942.22
   371.3 1937.72   390.9 1927.97   395.4 1926.09   404.2 1925.29   413.4 1925.93
   423.6 1928.05   430.7 1929.36   443.8 1933.47   451.4 1934.43   491.8 1932.41
   519.8 1932.81   535.8 1935.21   571.8 1934.51   591.8 1937.54   611.8 1938.83
   639.8 1946.79   691.7 1945.77   711.8 1947.64   739.8 1951.87   857.8 1949.08
#Mann= 6 ,-1 , 0
       0      .1       0   390.9    .045       0   423.6      .1       0
   488.1     .05       0  586.59      .1       0  685.08     .05       0
#XS Ineff= 2 , 0
          382.09    1929  439.47            1929
Permanent Ineff=
       F       F
Bank Sta=390.9,423.6
XS Rating Curve= 0 ,0
Exp/Cntr=0.5,0.3

Type RM Length L Ch R = 1 ,711     ,37.2,37.2,37.6
XS GIS Cut Line= 3
2405341.54835955626438.295978443 2405532.5510928626035.133286111
2405528.43718778625633.733695931
#Sta/Elev= 30
       0 2061.82      79 2027.97   216.2 1977.44   236.4 1968.05     255 1962.03
   283.1 1955.97   309.8 1947.58   324.8 1944.82     349 1942.44   366.7 1938.37
   388.8 1927.47   393.3 1925.83   402.1 1925.05   413.9 1925.63   420.9 1927.56
   450.4 1933.24   498.4 1931.85   522.4 1932.24   542.4 1935.27   574.4  1934.4
   594.4 1936.98   602.4 1936.42   618.4 1938.78   642.4 1945.31   694.4 1945.93
   734.4 1952.24   746.4 1952.32   766.4 1950.56   798.4 1949.27   847.5 1948.54
#Mann= 6 ,-1 , 0
       0      .1       0   388.8    .045       0   420.9      .1       0
  492.27     .05       0  590.82      .1       0  689.37     .05       0
Bank Sta=388.8,420.9
XS Rating Curve= 0 ,0
Exp/Cntr(USF)=0,0
Exp/Cntr=0.5,0.3

Type RM Length L Ch R = 1 ,674     ,127.7,115.6,101.8
XS GIS Cut Line= 3
2405372.25309985  626447.10058042405567.94071765  626048.1405534
2405546.70330177625630.977027069
#Sta/Elev= 30
       0 2044.03    40.3 2027.48   132.8 1985.78   169.2 1976.36   205.5 1963.05
   258.6  1945.9     271 1942.94   294.3 1939.64   361.1 1939.28     369 1936.57
   378.6 1926.88   383.4 1924.87   392.3 1923.96   402.6 1924.36   410.1 1926.65
   427.9 1926.88   461.9 1931.98   485.7 1932.38   501.7 1931.16   517.7 1931.99
   549.9 1929.39   565.8 1930.55   577.8 1933.27   606.8 1933.14   633.9 1937.46
   653.9 1942.39     738 1953.31     750  1953.4   794.1 1948.38   862.1 1947.42
#Mann= 6 ,-1 , 0
       0      .1       0   378.6    .045       0   410.1      .1       0
  508.67     .05       0  606.72      .1       0  704.78     .05       0
#XS Ineff= 2 , 0
                          504.11         1943.94
Permanent Ineff=
       F       F
Bank Sta=378.6,410.1
XS Rating Curve= 0 ,0
Exp/Cntr(USF)=0,0
Exp/Cntr=0.3,0.1

Type RM Length L Ch R = 1 ,558     ,87.9,87.4,88.7
XS GIS Cut Line= 3
2405766.48601603626343.2099492322405604.64173739625950.059872433
2405572.69459607625637.960876404
#Sta/Elev= 30
       0 1925.34   114.9 1932.53   147.1 1932.65     221 1935.82   233.9 1934.98
   238.3  1933.1   248.2 1925.83   254.4 1923.36     283 1922.35   293.5 1920.19
     304 1921.01   315.7 1920.13   327.9 1920.96   331.9 1922.34   346.3 1928.27
   355.1 1929.17     407 1930.76   464.5 1928.68   480.6 1931.57   500.7 1931.45
   516.8  1935.2   532.9 1941.95     553 1947.86   609.3 1952.56   625.4 1953.43
   641.5 1952.31   673.6 1947.03   681.9  1946.5   701.8 1945.66   738.9  1946.6
#Mann= 6 ,-1 , 0
       0      .1       0     283    .045       0   331.9      .1       0
  397.06     .05       0  495.46      .1       0  593.13     .05       0
Bank Sta=283,331.9
XS Rating Curve= 0 ,0
Exp/Cntr(USF)=0,0
Exp/Cntr=0.5,0.3

Type RM Length L Ch R = 1 ,471     ,38.9,41.7,33.9
XS GIS Cut Line= 3
2405846.85957165626314.1963609852405700.76866086625959.673446566
 2405563.1422562625659.577082845
#Sta/Elev= 30
       0 1924.18    94.8 1929.17   124.7 1932.06     181  1931.2   219.9 1931.94
   241.5 1930.36   258.8 1931.24   280.5 1929.08   294.3 1926.32   297.8  1924.8
   305.9 1919.66   315.1 1918.31   351.9 1918.51   359.1 1919.42     380 1925.17
   391.6 1926.02   397.6  1926.3   410.7 1925.23   432.7 1926.62   463.5 1924.97
   472.3 1925.57   481.1 1928.63   489.9  1930.5   520.7 1944.87   536.4 1948.19
   613.1 1952.72   630.7 1952.07   666.1 1946.85   696.7    1946   713.6 1947.48
#Mann= 4 ,-1 , 0
       0      .1       0  279.96     .05       0   305.9    .045       0
   359.1     .05       0
#XS Ineff= 2 , 0
          298.97    1926  373.72            1924
Permanent Ineff=
       F       F
Bank Sta=305.9,359.1
XS Rating Curve= 0 ,0
Exp/Cntr=0.5,0.3

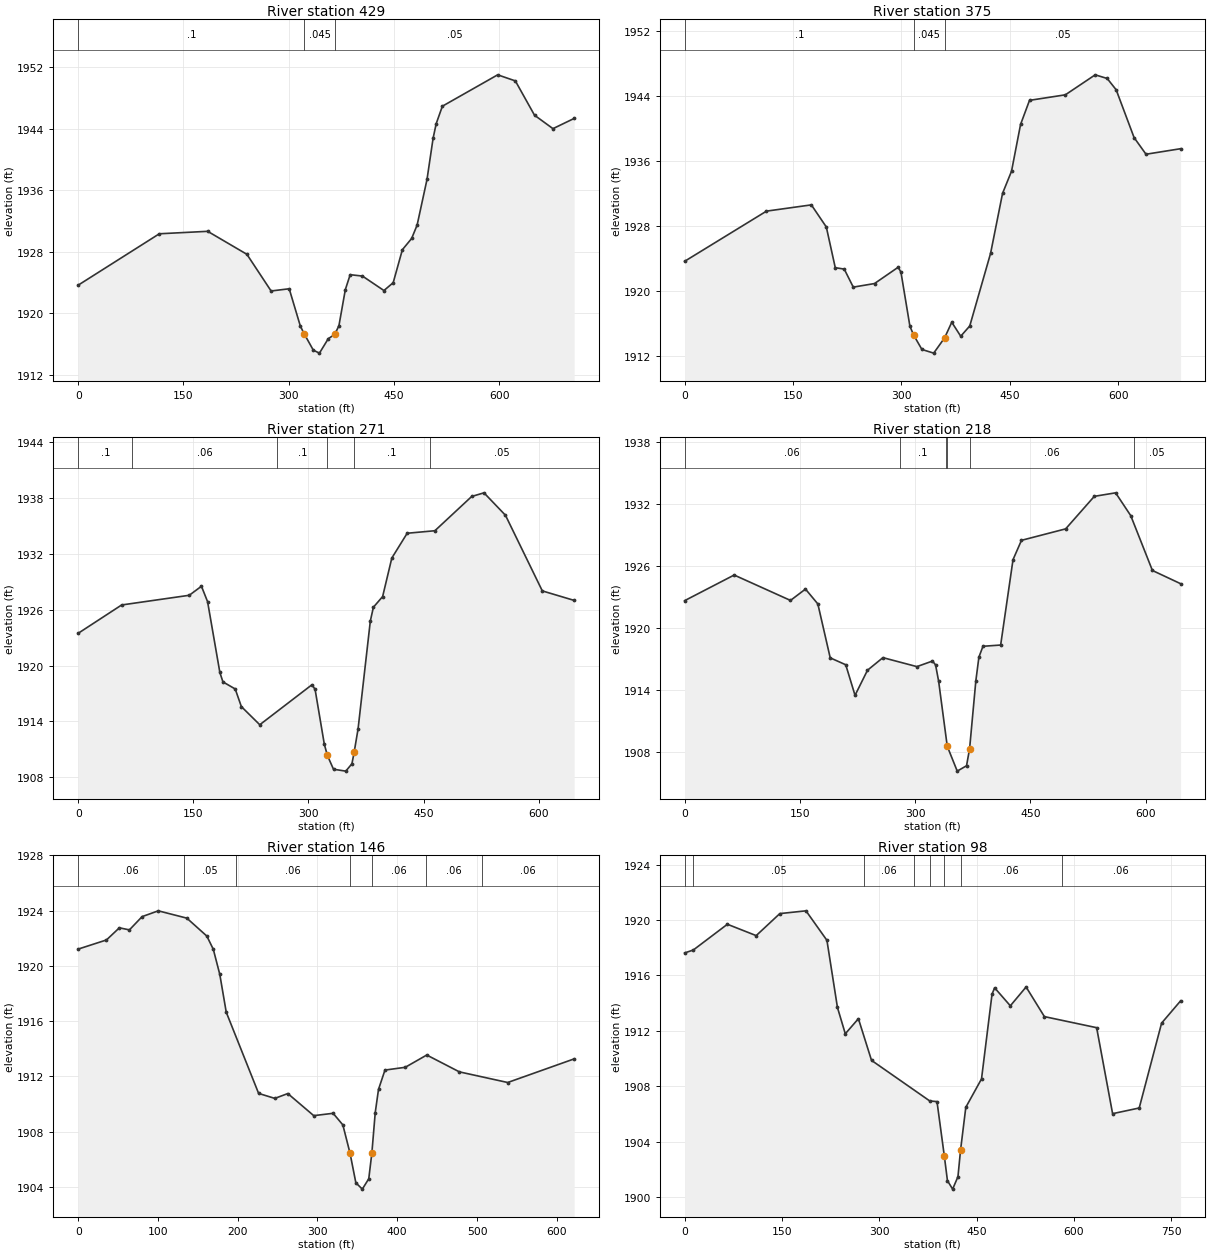
Type RM Length L Ch R = 1 ,429     ,50.8,54.4,55.8
XS GIS Cut Line= 3
2405870.63689414626298.2699660742405744.19637361625980.601194922
 2405595.5975185625647.290971633
#Sta/Elev= 30
       0 1923.65   115.6 1930.33   184.5 1930.65   240.4 1927.66   274.9 1922.89
   300.7 1923.18   316.6 1918.32   322.2  1917.3   335.1 1915.19   343.8 1914.81
   356.4 1916.69   365.7 1917.25   371.6 1918.39   380.7 1923.07   387.6 1925.01
   405.1 1924.83   435.7 1922.95   448.9 1923.97     462 1928.26   475.2 1929.72
     483 1931.46   497.1  1937.4   505.8 1942.76   510.2 1944.65     519 1946.92
   597.8    1951     623 1950.21   650.3 1945.75   676.6    1944   706.8 1945.33
#Mann= 3 ,-1 , 0
       0      .1       0   322.2    .045       0   365.7     .05       0
Bank Sta=322.2,365.7
XS Rating Curve= 0 ,0
Exp/Cntr=0.5,0.3

Type RM Length L Ch R = 1 ,375     ,96.4,103.4,107.7
XS GIS Cut Line= 2
2405878.03078882626288.4285492032405703.85743179625624.579239815
#Sta/Elev= 30
       0 1923.69   113.2 1929.86   175.3 1930.63     196 1927.91   208.4  1922.9
   220.8 1922.73   233.3 1920.51   262.7 1920.95   295.5 1922.96   299.3 1922.34
   311.7 1915.69   317.1 1914.57   328.3 1912.84   344.6 1912.39   359.7 1914.27
   369.6 1916.19     382 1914.47   394.5 1915.73   423.3 1924.66   439.9 1932.05
   452.3 1934.77   464.8 1940.52   477.2 1943.49   526.8 1944.17   568.1 1946.63
   584.7 1946.18   597.1 1944.79   621.9 1938.91   638.4 1936.86   686.3 1937.54
#Mann= 3 ,-1 , 0
       0      .1       0   317.1    .045       0   359.7     .05       0
Bank Sta=317.1,359.7
XS Rating Curve= 0 ,0
Exp/Cntr(USF)=0,0
Exp/Cntr=0.3,0.1

Type RM Length L Ch R = 1 ,271     ,51.3,52.8,53.9
XS GIS Cut Line= 2
2405882.01189413626291.4143781812405902.91269697 625645.48004266
#Sta/Elev= 30
       0 1923.46    56.6  1926.5   144.7 1927.54   160.6 1928.51   168.6 1926.85
   184.6 1919.25   188.6 1918.24   204.6 1917.48   212.6 1915.59   236.6 1913.64
   304.7 1917.94   308.7 1917.43   320.7 1911.56   324.7 1910.34   332.7 1908.86
   348.7 1908.66   356.7 1909.45   359.6 1910.69   364.7 1913.19   380.7 1924.79
   384.7 1926.26   396.7  1927.4   408.7 1931.54   428.7  1934.2   464.8 1934.47
   512.8 1938.15   528.8 1938.54   556.8 1936.13   604.8 1928.01   646.3 1926.99
#Mann= 6 ,-1 , 0
       0      .1       0   70.74     .06       0  259.55      .1       0
   324.7    .045       0   359.6      .1       0  458.05     .05       0
Bank Sta=324.7,359.6
XS Rating Curve= 0 ,0
Exp/Cntr(USF)=0,0
Exp/Cntr=0.5,0.3

Type RM Length L Ch R = 1 ,218     ,71.1,72,72.4
XS GIS Cut Line= 2
2405900.76716276626302.7981807172405981.86375228625662.535600501
#Sta/Elev= 30
       0 1922.61    64.4 1925.09   137.7 1922.63   157.2 1923.73   173.3 1922.29
   189.4 1917.07   209.6  1916.4   221.7 1913.44   237.9 1915.87     258 1917.09
   302.2 1916.22   322.5 1916.76   326.5 1916.39   330.5  1914.8   341.7 1908.51
   354.7  1906.1   366.8 1906.62   370.8 1908.28   378.9 1914.84   382.9 1917.14
   388.2 1918.19   411.2 1918.31   427.3 1926.58   438.3 1928.45   495.8 1929.56
   533.1 1932.71   560.8 1933.05   580.5 1930.84   608.7 1925.53   645.4 1924.25
#Mann= 6 ,-1 , 0
       0     .06       0  280.09      .1       0  340.14     .06       0
   341.7    .045       0   370.8     .06       0  584.56     .05       0
#XS Ineff= 2 ,-1
       0  322.69  1915.5  385.93645.3781  1914.7
Permanent Ineff=
       F       F
Bank Sta=341.7,370.8
XS Rating Curve= 0 ,0
Exp/Cntr(USF)=0,0
Exp/Cntr=0.5,0.3

Type RM Length L Ch R = 1 ,146     ,48,47.9,47.2
XS GIS Cut Line= 3
2405955.35991234626309.7723963982406033.47067288625861.590865684
 2406057.2315262625696.397586446
#Sta/Elev= 30
       0 1921.22    35.4 1921.88    51.6 1922.76    64.2 1922.61    80.1 1923.57
   100.4 1923.99   136.2 1923.46   161.3 1922.16   169.4  1921.2   177.5 1919.39
   185.6 1916.65   226.2 1910.77   246.5 1910.41   262.8 1910.76   295.3 1909.16
   319.6 1909.33   331.8 1908.49   340.8 1906.44   348.1  1904.3   356.2 1903.84
   364.3 1904.59   368.2 1906.47   372.4 1909.38   376.5 1911.06   384.6 1912.46
     410 1912.66     437 1913.55   477.9 1912.33   538.5 1911.56   621.8 1913.27
#Mann= 7 ,-1 , 0
       0     .06       0  132.74     .05       0  197.36     .06       0
   340.8    .045       0   368.2     .06       0  436.31     .06       0
  505.81     .06       0
Bank Sta=340.8,368.2
XS Rating Curve= 0 ,0
Exp/Cntr(USF)=0,0
Exp/Cntr=0.5,0.3

Type RM Length L Ch R = 1 ,98      ,,,
XS GIS Cut Line= 3
2406006.82645969626380.1178080762406088.74220668625779.402330156
2406081.15741529625621.638669288
#Sta/Elev= 30
       0 1917.63    13.3 1917.84    65.8  1919.7   110.2 1918.88   146.6 1920.47
   186.9 1920.67   219.2 1918.54   235.4 1913.69   247.5 1911.79   267.7 1912.88
   287.9 1909.87   377.6 1906.94   388.8 1906.89     4001902.994   404.9 1901.18
   412.9 1900.57   421.1 1901.47   425.1 1903.39   433.2 1906.48   457.4 1908.53
   473.6 1914.65   477.6 1915.11   501.8 1913.81   526.1 1915.17   554.3 1913.03
   634.8 1912.23   659.4 1906.02   700.4 1906.43   734.9 1912.56   764.2 1914.17
#Mann= 8 ,-1 , 0
       0     .06       0    13.3     .05       0  275.82     .06       0
  353.48     .05       0   377.6     .06       0     400    .045       0
   425.1     .06       0  581.14     .06       0
Bank Sta=400,425.1
XS Rating Curve= 0 ,0
Exp/Cntr(USF)=0,0
Exp/Cntr=0.3,0.1
LCMann Table=0

Chan Stop Cuts=-1
Use User Specified Reach Order=0
Composite Channel Slope=5